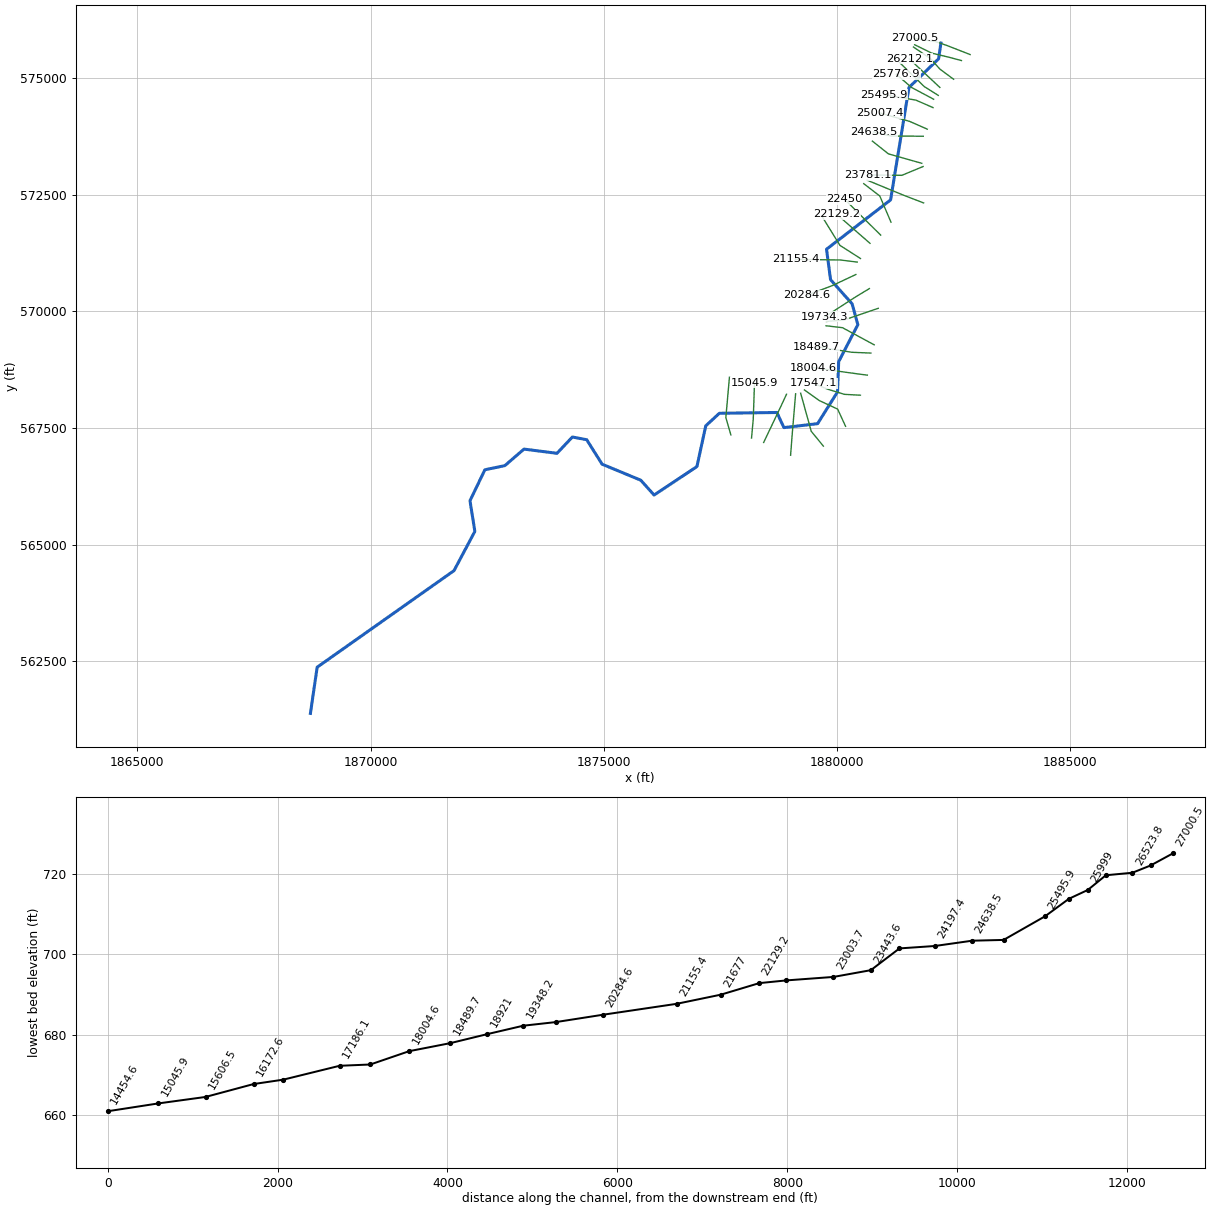
--- HurrcneCrk.prj (project) ---

Proj Title=HurrcneCrk
Current Plan=p01
Default Exp/Contr=0,0
English Units
Geom File=g01
Flow File=f01
Plan File=p01
BEGIN DESCRIPTION:
AMEC Environment & Infrastructure, 2013
Projection: NAD 1983 State Plane West Virginia South FIPS 4702 (US Feet)
Vertical Datum: NAVD 1988
END DESCRIPTION:
DSS File=dss
DSS Export Rating Curves= 0
DSS Export Rating Curve Sorted= 0
DSS Export Volume Flow Curves= 0
DXF OffsetX= 0
DXF OffsetY= 0
DXF ScaleX= 0
DXF ScaleY= 0

--- HurrcneCrk.p01 (plan) ---

Plan Title=Floodplain
Program Version=4.10
Short Identifier=Floodplain
Geom File=g01
Flow File=f01
Subcritical Flow
K Sum by GR= 0
Std Step Tol= 0.01
Critical Tol= 0.01
Num of Std Step Trials= 20
Max Error Tol= 0.3
Flow Tol Ratio= 0.001
Split Flow NTrial= 30
Split Flow Tol= 0.02
Split Flow Ratio= 0.02
Log Output Level= 0
Friction Slope Method= 1
Unsteady Friction Slope Method= 2
Unsteady Bridges Friction Slope Method= 1
Parabolic Critical Depth
Global Vel Dist= 0 , 0 , 0
Global Log Level= 0
CheckData=True
Encroach Param=-1 ,0,0, 0
Run HTab= 0
Run UNet= 0
Run PostProcess= 0
Run WQNet= 0
UNET Theta= 0
UNET Theta Warmup= 0
UNET ZTol= 0
UNET ZSATol= 0
UNET MxIter= 0
UNET MaxInSteps= 0
UNET DtIC= 0
UNET DtMin= 0
UNET MaxCRTS= 0
UNET WFStab= 0
UNET SFStab= 0
UNET WFX= 1
UNET SFX= 1
UNET DSS MLevel= 1
UNET DZMax Abort= 0
UNET Convert EG Bridges= 0
UNET Use Existing IB Tables= 0
UNET Froude Reduction=False
UNET Froude Limit= 0
UNET Froude Power= 0
UNET Time Slicing=0,0, 5
UNET Junction Losses=0
DSS File=dss
Write IC File= 0
Write IC File at Sim End=0
Echo Input=False
Echo Parameters=False
Echo Output=False
Write Detailed= 0
WQ AD Non Conservative
WQ ULTIMATE=-1
WQ Max Comp Step=1HOUR
WQ Output Interval=15MIN
WQ Output Selected Increments= 0
WQ Output face flow=0
WQ Output face velocity=0
WQ Output face area=0
WQ Output face dispersion=0
WQ Output cell volume=0
WQ Output cell surface area=0
WQ Output cell continuity=0
WQ Output cumulative cell continuity=0
WQ Output face conc=0
WQ Output face dconc_dx=0
WQ Output face courant=0
WQ Output face peclet=0
WQ Output face adv mass=0
WQ Output face disp mass=0
WQ Output cell mass=0
WQ Output cell source sink temp=0
WQ Output cell source sink nsm=0
WQ Output MaxMinRange=-1
WQ Daily Max Min Mean=-1
WQ Daily Range=0
WQ Daily Time=0
WQ Create Restart=0
WQ Fixed Restart=0
WQ System Summary=0
WQ Use Fixed Temperature=0
Sorting and Armoring Iterations= 10
XS Update Threshold= 0.02
Hydraulics Update Threshold= 0.02
Energy Slope Method= 1
Volume Change Method= 0
XS Weighting Method= 0
Number of US Weighted Cross Sections= 1
Number of DS Weighted Cross Sections= 1
Upstream XS Weight=0.25
Main XS Weight=0.5
Downstream XS Weight=0.25
Number of DS XS's Weighted with US Boundary= 1
Upstream Boundary Weight= 1
Weight of XSs Associated with US Boundary= 0
Number of US XS's Weighted with DS Boundary= 1
Downstream Boundary Weight= 0.5
Weight of XSs Associated with DS Boundary= 0.5
Sediment Output Level= 4
Mass or Volume Output= 0
Output Increment Type= 1
Profile and TS Output Increment= 10
XS Output Flag= 0
XS Output Increment= 10
Disregard all LS=0
Disregard all Conn=0
Disregard all Breaches=0
Disregard all Pumps=0

--- HurrcneCrk.f01 (steady flow) ---

Flow Title=NFF Regression Equation
Program Version=4.10
Number of Profiles= 1
Profile Names=P100yr
River Rch & RM=HurrcneCrk,Main            ,27000.5
1099.669
River Rch & RM=HurrcneCrk,Main            ,25495.9
1126.260
River Rch & RM=HurrcneCrk,Main            ,23781.1
1248.928
River Rch & RM=HurrcneCrk,Main            ,23443.6
1456.393
River Rch & RM=HurrcneCrk,Main            ,19734.3
1517.867
River Rch & RM=HurrcneCrk,Main            ,14454.6
1686.299
River Rch & RM=HurrcneCrk,Main            ,14117.8
1878.896
River Rch & RM=HurrcneCrk,Main            ,9667.1
2014.925
River Rch & RM=HurrcneCrk,Main            ,1336.7
2231.218
River Rch & RM=HurrcneCrk,Main            ,980.6
3661.633
River Rch & RM=HurrcneCrk,Main            ,672.9
4769.873
River Rch & RM=HurrcneCrk,Main            ,350.7
4770.603
River Rch & RM=HurrcneCrk,Main            ,8.8
5204.667
Boundary for River Rch & Prof#=HurrcneCrk,Main            , 1
Up Type= 0
Dn Type= 3
Dn Slope=0.00329
DSS Import GetInterval= 0
DSS Import GetPeak= 0
DSS Import FillOption= 0

--- HurrcneCrk.g01 (geometry) ---

Geom Title=USGS 3m DEM
Program Version=4.10

River Reach=HurrcneCrk      ,Main
Reach XY= 30
     1882230.524      575749.326     1882180.603      575410.667
     1881546.102       574798.41     1881151.259      572388.342
     1879777.775       571332.39     1879864.629      570679.393
     1880326.606      570161.869     1880449.924      569715.541
     1880038.348      568923.595     1880014.053      568275.805
     1879586.844      567595.008      1878864.38       567509.89
     1878713.486      567833.841     1877480.223      567817.246
     1877188.466       567548.05     1876999.237      566675.548
     1876080.496      566064.879     1875795.669      566382.687
     1874965.518      566726.528     1874635.723      567250.808
     1874328.134      567308.303     1873998.172      566959.217
     1873291.334      567049.504     1872879.748      566695.207
     1872452.523      566606.622     1872132.992      565943.196
     1872237.212      565286.728     1871790.907      564446.155
     1868856.077      562376.388      1868711.37      561387.308

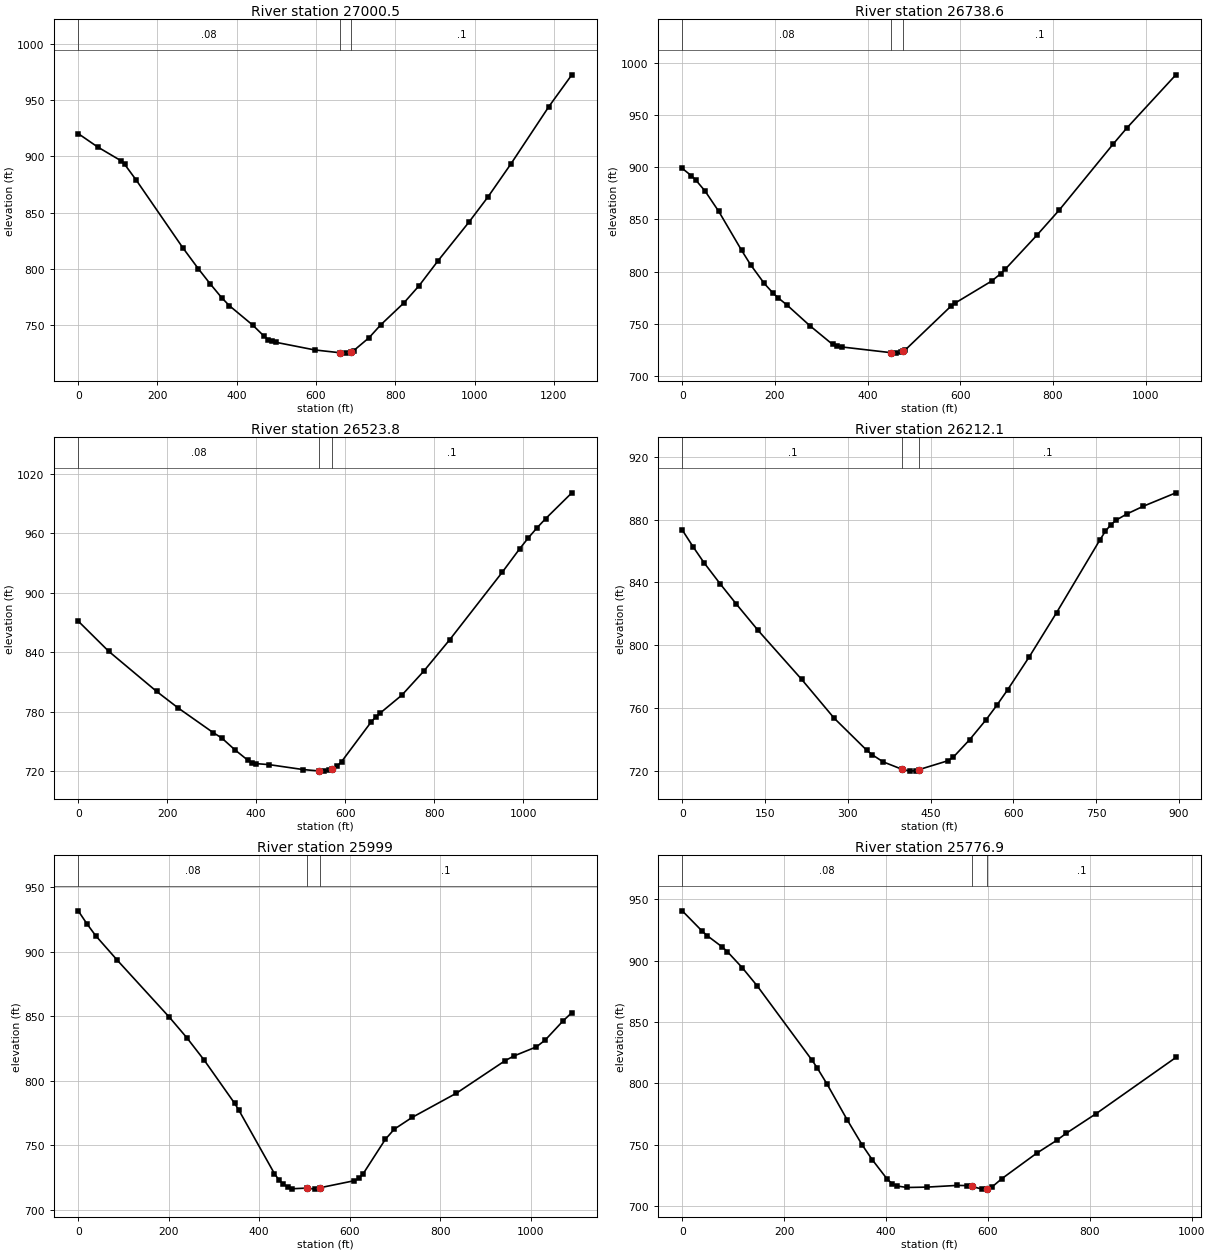
Type RM Length L Ch R = 1 ,27000.5 ,259.2,261.8,264.4
XS GIS Cut Line= 4
     1882857.668      575502.744     1882347.392      575702.138
     1882105.767      575782.323     1881667.836       575850.57
#Sta/Elev= 30
       0  920.14    48.9  908.29   107.6  896.09   117.4  892.72   146.8   878.6
   264.1  818.59   303.3  799.94   332.6  786.79     362   774.3   381.5  767.17
   440.2  749.98   469.6   739.9   479.4  737.09   489.2  735.43   498.9  734.64
   596.8  727.86   659.8   725.4   675.1  725.03  687.83  725.79   694.7  727.13
   733.9  738.73   763.3  750.14   821.7  769.64   860.2  784.98   908.4  807.31
   985.5  841.25  1033.7  863.72  1091.5  893.02  1187.8  944.22  1245.6  972.38
#Mann= 3 , 0 , 0
       0     .08       0   659.8    .045       0  687.83      .1       0
Bank Sta=659.8,687.83
XS Rating Curve= 0 ,0
Exp/Cntr=0.3,0.1

Type RM Length L Ch R = 1 ,26738.6 ,233.1,214.8,196.6
XS GIS Cut Line= 4
     1882671.239      575374.285     1882405.142      575445.244
     1882032.607      575533.943     1881667.675      575713.875
#Sta/Elev= 30
       0  898.76    19.7  891.73    29.5  887.45    49.2  877.11    78.7  857.68
   127.9  820.51   147.5  806.56     177  788.68   196.7  779.08   206.6  775.05
   226.2  767.99   275.4  748.26   324.5  730.36   334.3  728.65   344.1  727.94
   449.4  722.52     462  722.03   471.8  722.64  475.67  723.68   481.6  725.25
   579.8  766.94   589.6  770.12     668  791.07   687.4  798.12   697.1  802.36
   764.9  834.65   813.4  858.83   929.6  921.88   958.7  937.04  1065.2  988.27
#Mann= 3 , 0 , 0
       0     .08       0   449.4    .045       0  475.67      .1       0
Bank Sta=449.4,475.67
XS Rating Curve= 0 ,0
Exp/Cntr=0.3,0.1

Type RM Length L Ch R = 1 ,26523.8 ,309,311.7,314.4
XS GIS Cut Line= 4
      1882502.53      574974.385     1882211.434       575189.13
     1882006.159      575417.213     1881641.167      575664.417
#Sta/Elev= 30
       0  871.33    68.4  840.98     176  800.59   224.9  783.75   303.1  759.09
   322.6  753.59     352  741.74   380.9  731.32   390.5  728.82   400.1  727.77
   428.9  726.77   505.6  721.79   541.3  720.39   553.5  720.22   563.1  720.88
   571.3  722.21   582.3  725.32   591.9  729.81     659  770.11   668.6  774.72
   678.4   778.6   727.4  796.78   776.4  820.82   835.1  852.68   952.7  920.38
   991.9  944.05  1011.5  955.14    1031  965.24  1050.6  974.58  1109.4 1000.56
#Mann= 3 , 0 , 0
       0     .08       0   541.3    .045       0   571.3      .1       0
Bank Sta=541.3,571.3
XS Rating Curve= 0 ,0
Exp/Cntr=0.3,0.1

Type RM Length L Ch R = 1 ,26212.1 ,213.6,213,212.4
XS GIS Cut Line= 2
     1882207.471       574799.01     1881553.633      575409.765
#Sta/Elev= 30
       0  873.35    19.7  862.62    39.3  852.57    68.8  838.98    98.3     826
   137.6  809.28   216.3  778.15   275.3  753.38   334.3  732.95   344.1   730.1
   363.8  725.56   398.8  720.71     413   719.6   422.8   719.9   428.8  720.52
   481.8  726.25   491.6  728.62   521.1  739.72   550.6  752.32   570.3  761.65
   589.9  771.54   629.2   792.6   678.4   820.6   757.1  867.08   766.9  872.51
   776.7   876.7   786.6  879.66   806.2  883.63   835.7   888.5   894.7  897.05
#Mann= 3 , 0 , 0
       0      .1       0   398.8    .045       0   428.8      .1       0
Bank Sta=398.8,428.8
XS Rating Curve= 0 ,0
Exp/Cntr=0.3,0.1

Type RM Length L Ch R = 1 ,25999   ,220.4,221.8,223.3
XS GIS Cut Line= 3
     1882173.737       574628.32     1881873.005      574817.545
      1881345.88      575331.154
#Sta/Elev= 30
       0   931.7    19.2  921.67    38.4  912.51    86.4   893.4   201.7  849.14
   240.1  833.32   278.5  815.94   345.7  782.51   355.3  777.06   433.8  727.97
   443.6  723.12   453.4  719.88   463.2  717.53   473.1  716.23   505.3  716.75
   523.6  715.94   535.3  717.07   610.4  722.47   620.3   724.2   630.1  727.93
   679.1   754.6   698.8  762.43     738   771.5   836.2  790.33   944.1   815.6
   963.7  819.24  1012.8   826.2  1032.4   831.5  1071.7  846.29  1091.3  852.76
#Mann= 3 , 0 , 0
       0     .08       0   505.3    .045       0   535.3      .1       0
Bank Sta=505.3,535.3
XS Rating Curve= 0 ,0
Exp/Cntr=0.3,0.1

Type RM Length L Ch R = 1 ,25776.9 ,264.5,281,297.4
XS GIS Cut Line= 3
     1882075.689      574545.584      1881599.25       574799.01
     1881274.865      575080.312
#Sta/Elev= 30
       0  940.64    39.2  924.04    49.1  920.34    78.5  911.17    88.3  907.46
   117.7  894.32   147.2  879.43   255.1  818.66   264.9  812.59   284.5  799.23
   323.8  770.25   353.2   749.8   372.8  737.83   402.3  721.92   412.1  718.18
   421.9  716.28   441.5  715.08   480.8   715.4   539.6  716.78   559.2  716.63
   568.7  715.96   588.4  713.75   598.7  713.84     608  715.48   627.5  722.31
   695.8  743.03   734.8  753.42   754.3  759.41   812.9   775.4     969  821.07
#Mann= 3 , 0 , 0
       0     .08       0   568.7    .045       0   598.7      .1       0
Bank Sta=568.7,598.7
XS Rating Curve= 0 ,0
Exp/Cntr=0.3,0.1

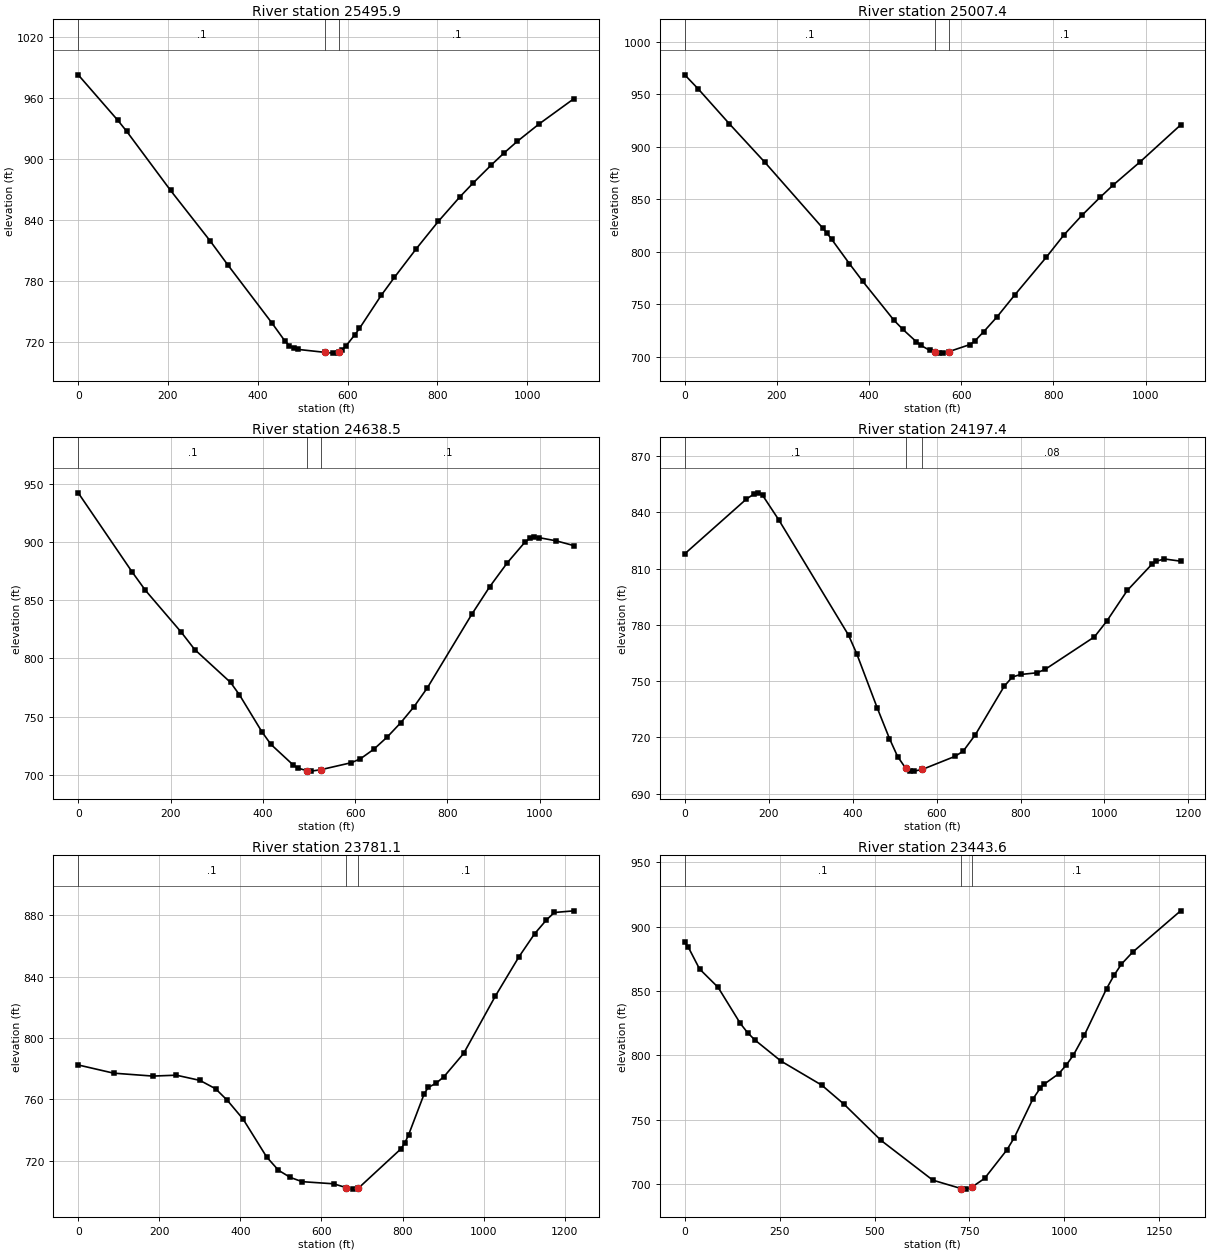
Type RM Length L Ch R = 1 ,25495.9 ,491.8,488.5,485.1
XS GIS Cut Line= 3
     1882062.235      574366.162     1881693.918       574526.95
     1881001.222      574645.215
#Sta/Elev= 30
       0  982.41    88.2   937.8   107.8  927.08   205.8  868.97   294.1  819.36
   333.3  795.92   431.2  739.14   460.4   721.3   470.2  716.84     480  714.36
   489.7  713.05   550.5  710.11   567.8   709.4   577.6  709.78   580.5  710.49
   587.3  712.16   597.1  716.79   616.6  727.66   626.4  733.57   675.2  766.24
   704.4  783.74   753.2  811.88     802  838.56   850.8  862.99   880.1  876.45
   919.2  893.55   948.4  905.69   977.7  917.02  1026.5  934.16  1104.6  959.12
#Mann= 3 , 0 , 0
       0      .1       0   550.5    .045       0   580.5      .1       0
Bank Sta=550.5,580.5
XS Rating Curve= 0 ,0
Exp/Cntr=0.3,0.1

Type RM Length L Ch R = 1 ,25007.4 ,360.7,368.8,376.9
XS GIS Cut Line= 3
     1881938.747        573904.6     1881558.702      574071.679
     1880922.604      574251.611
#Sta/Elev= 30
       0  968.36      29  955.08    96.6  921.86   173.8  885.16   299.3  822.63
     309  817.55   318.6  811.98   357.2  788.76   386.2  771.92     454  734.83
   473.5  726.08   502.6  714.38   512.4  710.96   531.8  706.13   542.7  704.32
   551.2  703.52     561  703.57   572.7  704.86   619.3  711.71     629  714.83
   648.5  723.74   677.6  737.93   716.5  759.03   784.6  794.74   823.4  816.23
   862.3  834.76   901.2  851.69   930.4  863.69   988.7   885.7  1076.2  920.66
#Mann= 3 , 0 , 0
       0      .1       0   542.7    .045       0   572.7      .1       0
Bank Sta=542.7,572.7
XS Rating Curve= 0 ,0
Exp/Cntr=0.3,0.1

Type RM Length L Ch R = 1 ,24638.5 ,449.1,441,432.9
XS GIS Cut Line= 3
     1881852.731      573753.158     1881163.414      573756.537
     1880788.344      573844.391
#Sta/Elev= 30
       0  942.14   116.5  874.43   145.6  858.48   223.3  822.54   252.4  807.68
   330.1  779.46   349.5  768.75   398.1  737.07   417.5  726.34     466  708.55
   475.7  706.07   495.1  703.68   504.9  703.33   525.1   704.5   592.2   710.6
   611.6  713.93   640.8  722.18   669.9  732.69     699  744.89   727.8  758.65
   756.7  774.87     853  837.97   891.6  861.48   930.1  882.24   968.6  900.04
   978.2  902.95   987.9  904.03   997.5  903.76    1036  900.92  1074.6   896.8
#Mann= 3 , 0 , 0
       0      .1       0   495.1    .045       0   525.1      .1       0
Bank Sta=495.1,525.1
XS Rating Curve= 0 ,0
Exp/Cntr=0.3,0.1

Type RM Length L Ch R = 1 ,24197.4 ,408.3,416.3,424.3
XS GIS Cut Line= 3
     1881819.507      573173.616     1881105.971      573374.709
     1880761.312      573648.409
#Sta/Elev= 30
       0  817.84   146.3  846.91   165.8  849.86   175.6  850.35   185.3   849.1
   224.4  835.81   390.2   774.5   409.7  764.62   458.5  735.77   487.7  719.39
   507.2  709.76   526.7  703.46   536.5  702.17   546.2  702.01   565.8   702.9
   643.8  709.88   663.3  712.62   692.6   721.5   760.9  747.17   780.4  752.16
     800  753.52   839.1  754.42   858.7  756.26   976.1  773.58  1005.4  781.94
  1054.3  798.32    1113  812.28  1122.8  813.83  1142.3  815.11  1181.4  813.92
#Mann= 3 , 0 , 0
       0      .1       0   526.7    .045       0   565.8     .08       0
Bank Sta=526.7,565.8
XS Rating Curve= 0 ,0
Exp/Cntr=0.3,0.1

Type RM Length L Ch R = 1 ,23781.1 ,348.9,337.1,326.1
XS GIS Cut Line= 3
     1881849.352      573104.389     1881393.186      572915.165
     1880664.021      572923.698
#Sta/Elev= 30
       0  782.39    87.2  777.05     184  775.14   242.1  775.72   300.2  772.33
   338.9  766.86     368  759.26   406.7  747.07   464.8  722.37   493.9  713.73
     523  709.05   552.2  706.28     630  704.88   660.8  702.41   678.6  701.41
   690.8  701.97   795.3   727.5     805  731.22   814.7  736.68   853.6  763.73
   863.3  767.72   882.8  770.49   902.2  774.77   950.8  789.96  1028.6  827.17
    1087  852.89  1125.8  867.98    1155  877.02  1174.5  881.84  1223.1  882.92
#Mann= 3 , 0 , 0
       0      .1       0   660.8    .045       0   690.8      .1       0
Bank Sta=660.8,690.8
XS Rating Curve= 0 ,0
Exp/Cntr=0.3,0.1

Type RM Length L Ch R = 1 ,23443.6 ,460.7,439.8,416.4
XS GIS Cut Line= 3
     1881859.489      572323.839      1881413.46      572496.168
     1880647.666      572811.352
#Sta/Elev= 30
       0  887.68     9.8  883.72      39  867.04    87.8  852.78   146.4  824.73
   165.9   817.4   185.4  811.72   253.7  795.45   361.1  776.74   419.6  761.97
   517.1  733.86   653.5  702.96     728  696.45   741.2     696     758  697.86
   789.9  704.34   848.4  726.38   867.9  735.86   916.6  765.73   936.1  774.29
   945.8  777.33   984.8  785.55  1004.3  792.08  1023.8  800.11    1053  815.81
  1111.4  851.83  1130.9  862.12  1150.4  870.81  1179.6  880.01  1306.3   912.2
#Mann= 3 , 0 , 0
       0      .1       0     728    .045       0     758      .1       0
Bank Sta=728,758
XS Rating Curve= 0 ,0
Exp/Cntr=0.3,0.1

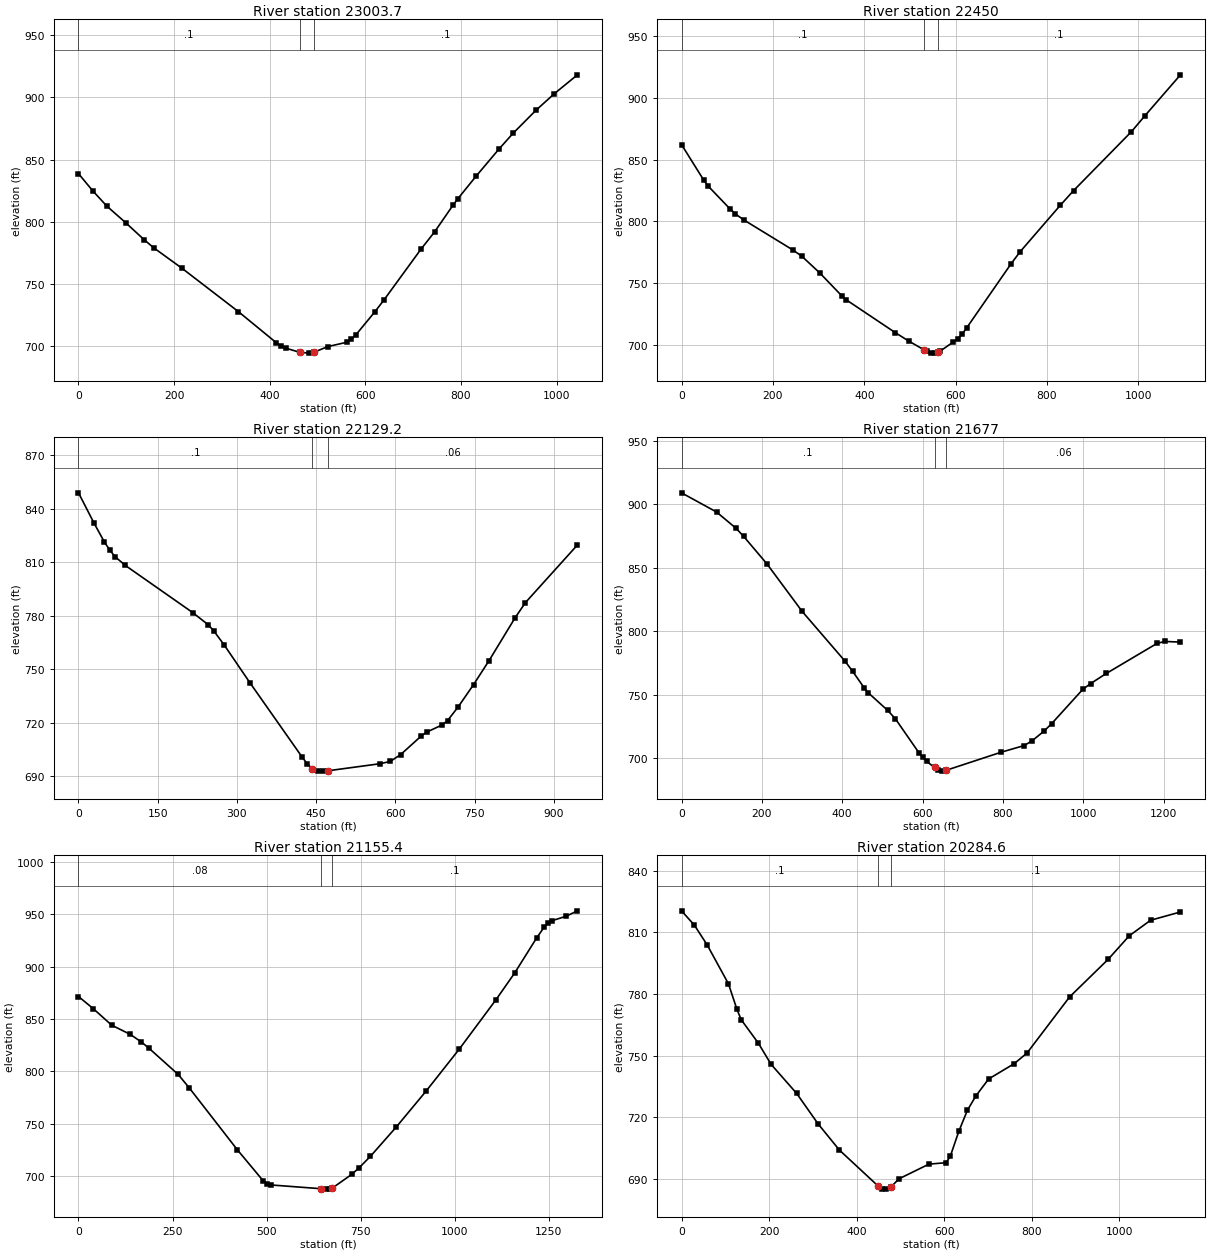
Type RM Length L Ch R = 1 ,23003.7 ,541.6,553.4,565
XS GIS Cut Line= 3
     1881160.035        571911.6     1880920.126      572472.515
     1880576.354      572736.446
#Sta/Elev= 30
       0  838.69    29.5  825.04      59  812.68    98.4  799.35   137.8  785.38
   157.4  779.03   216.5  762.57   334.6  727.65   413.3  702.82   423.1   700.2
     433  698.37   462.8  694.99   482.2  694.32   492.8  695.08   521.5  699.59
   560.9  703.04   570.7   705.4   580.6  709.26   619.7  727.49     639  737.15
     716   777.8   744.9  791.95   783.4   813.4   793.1  818.39   831.6   836.7
   879.7  858.61   908.6  871.06   956.8   889.7   995.3  903.07  1043.5   918.2
#Mann= 3 , 0 , 0
       0      .1       0   462.8    .045       0   492.8      .1       0
Bank Sta=462.8,492.8
XS Rating Curve= 0 ,0
Exp/Cntr=0.3,0.1

Type RM Length L Ch R = 1 ,22450   ,319.8,320.7,322.8
XS GIS Cut Line= 3
     1880939.724      571634.313        1880551.      572017.753
     1880164.912      572403.821
#Sta/Elev= 30
       0   862.1    48.8  833.24    58.5  828.44   107.2  809.67     117  806.27
   136.5  801.12   243.8  776.85   263.3  771.79   302.3  758.41     351  739.69
   360.8   736.5     468  709.99   497.3  703.22   530.9   696.1   536.3  694.94
     546  693.64   555.8  693.46   560.9  694.23   565.5  694.93   594.8  702.47
   604.5  705.18   614.3   708.9     624  713.82   721.5  765.84     741   775.4
   828.8  812.93     858  824.87   984.8  872.58    1014  885.32    1092  918.49
#Mann= 3 , 0 , 0
       0      .1       0   530.9    .045       0   560.9      .1       0
Bank Sta=530.9,560.9
XS Rating Curve= 0 ,0
Exp/Cntr=0.3,0.1

Type RM Length L Ch R = 1 ,22129.2 ,461.1,452,443
XS GIS Cut Line= 2
     1880709.727      571458.863     1879997.601      572079.755
#Sta/Elev= 30
       0     849    29.5  831.96    49.2  821.32      59  816.97    68.9  813.24
    88.6  808.26   216.5  781.73     246  774.85   255.9  771.61   275.6  763.73
   324.8  742.32   423.2  700.78     433  696.91   442.9  694.08   452.7  692.94
   462.6  692.78   472.4  692.98   570.8  696.93   590.5  698.23   610.2   702.1
   649.5  712.62   659.4  714.68   688.9  718.76   698.8  721.16   718.4   728.6
     748  741.31   777.5  754.84   826.7  778.84   846.4  787.41   944.8  819.74
#Mann= 3 , 0 , 0
       0      .1       0   442.9    .045       0   472.4     .06       0
Bank Sta=442.9,472.4
XS Rating Curve= 0 ,0
Exp/Cntr=0.3,0.1

Type RM Length L Ch R = 1 ,21677   ,490.3,521.5,552.7
XS GIS Cut Line= 3
     1880505.878      571133.393     1880065.237      571414.886
     1879686.789      572026.486
#Sta/Elev= 30
       0  909.05    87.2  893.94   135.6  881.16   154.9  874.68     213  852.96
   300.2  815.72   406.7  776.64     426  768.49   455.1  755.34   464.8  751.62
   513.2  737.74   532.6  731.01   590.9  704.43   600.6  700.65   610.4  697.55
   629.8  692.78   639.5  690.74   649.2  689.91     659  690.59     795  704.73
   853.3  710.08   872.8  713.82   901.9  721.26   921.4  727.28   999.1  754.35
  1018.6  758.88  1057.4  766.81  1183.8   790.5  1203.2  792.02  1242.1   791.5
#Mann= 3 , 0 , 0
       0      .1       0   629.8    .045       0     659     .06       0
Bank Sta=629.8,659
XS Rating Curve= 0 ,0
Exp/Cntr=0.3,0.1

Type RM Length L Ch R = 1 ,21155.4 ,730.4,869.8,758.8
XS GIS Cut Line= 3
     1880436.278      571056.405     1880076.163      571101.533
     1879113.147      571114.204
#Sta/Elev= 30
       0  871.37    39.2  859.81    88.3     844   137.3  835.31   166.8  828.08
   186.4  822.33   264.8  797.07   294.3  784.25   421.9  725.28   490.7  695.63
   500.5  692.87   510.3  691.64     645  688.01   657.8  687.63   667.6  687.79
     675  688.74   726.6  701.82   746.2  708.15   775.7  718.86   844.5  746.88
   923.1  780.84  1011.6  821.03  1109.8  868.45    1159  893.72  1217.9  927.43
  1237.6  937.57  1247.4  941.25  1257.2  943.56  1296.6  948.05    1326  953.12
#Mann= 3 , 0 , 0
       0     .08       0     645    .045       0     675      .1       0
Bank Sta=645,675
XS Rating Curve= 0 ,0
Exp/Cntr=0.3,0.1

Type RM Length L Ch R = 1 ,20284.6 ,546.7,549.4,552.4
XS GIS Cut Line= 3
     1880406.351      570790.073      1879894.88      570549.547
     1879357.019      570347.325
#Sta/Elev= 30
       0  820.55    29.2  813.62    58.5  803.98   107.2  784.99   126.7  772.48
   136.4  767.47   175.4  756.09   204.6  745.74   263.1  731.54   311.8  716.77
   360.6  703.96   448.3  686.58     458  685.11   467.8  684.91   477.5  685.79
     497  689.96   565.2  697.09   604.2  697.79   613.9  700.86   633.4  713.04
   652.9  723.27   672.3   730.3   701.6   738.6     760  746.06   789.2  751.22
   886.6   778.6   974.3  796.84    1023  808.42  1071.6  815.96  1139.8     820
#Mann= 3 , 0 , 0
       0      .1       0   448.3    .045       0   477.5      .1       0
Bank Sta=448.3,477.5
XS Rating Curve= 0 ,0
Exp/Cntr=0.3,0.1

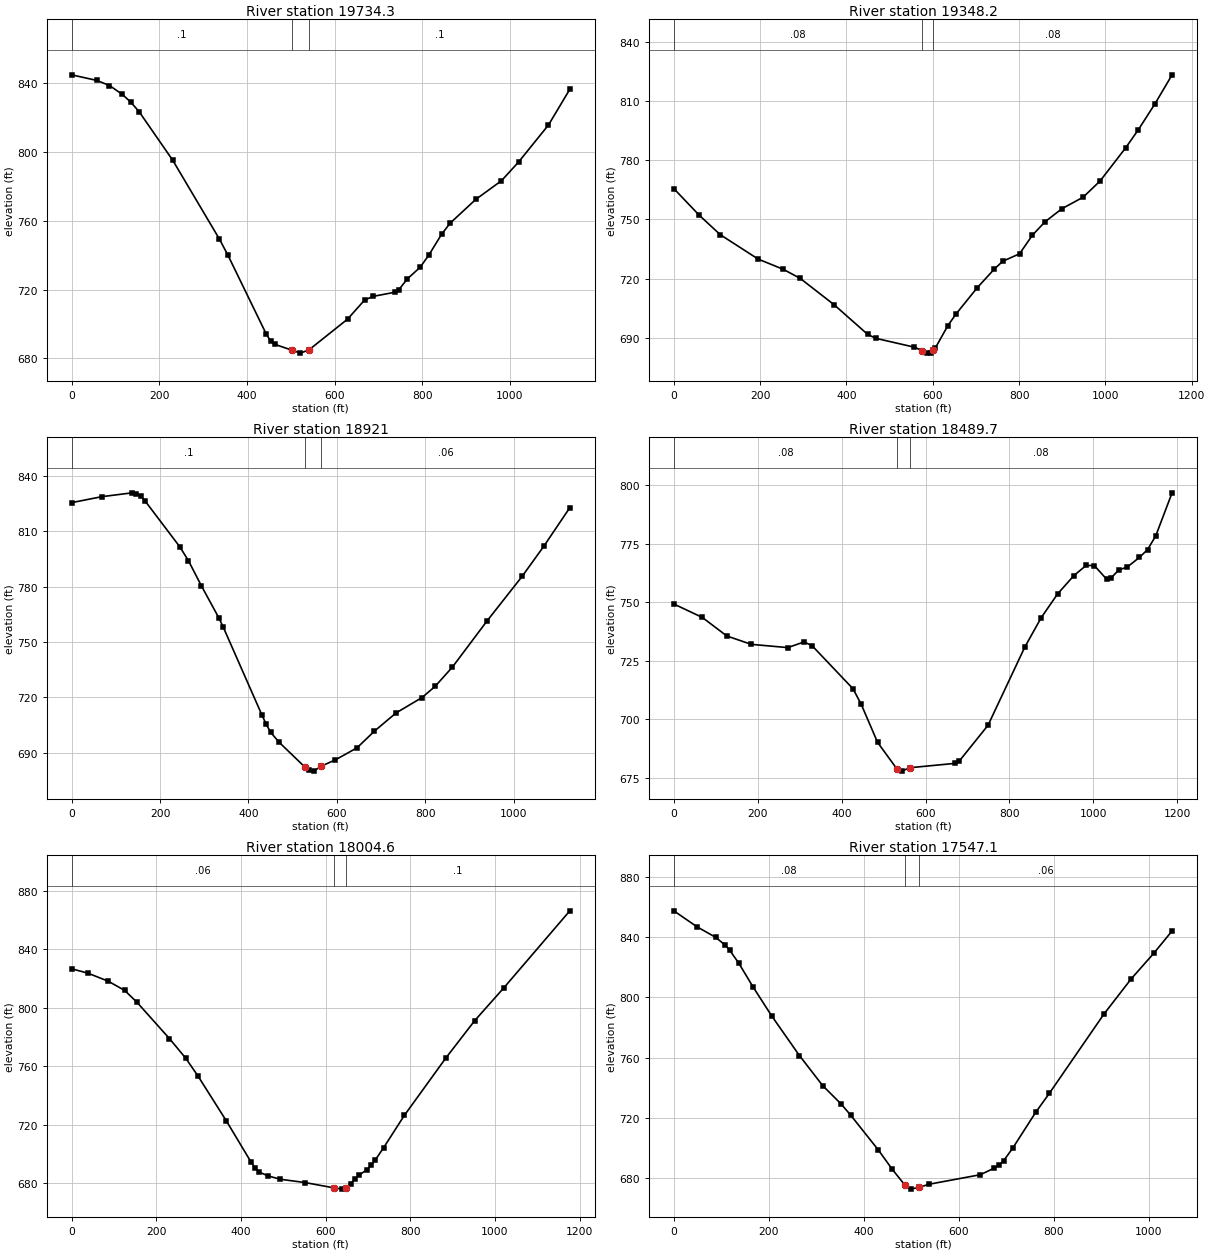
Type RM Length L Ch R = 1 ,19734.3 ,392.2,386.1,379.6
XS GIS Cut Line= 3
     1880697.111      570489.039     1880433.549      570330.226
     1879736.177      569881.779
#Sta/Elev= 30
       0  844.66    57.7   841.4    86.5  838.46   115.4  833.36   134.6  828.93
   153.9  823.34   230.8  795.06     337  749.43   356.5  740.07   444.3  694.11
     454  690.17   463.8  688.19   502.9   684.8   522.3   683.1   541.8  685.02
   629.6  702.81   668.6  713.93   688.1  716.05   736.9  718.41   746.7  719.91
   766.2  726.23   795.4  732.96   814.9  739.94   844.2  752.08   863.7  758.54
   922.2  772.34   980.8  783.18  1019.8  794.02  1088.1  815.54  1136.8  836.28
#Mann= 3 , 0 , 0
       0      .1       0   502.9    .045       0   541.8      .1       0
Bank Sta=502.9,541.8
XS Rating Curve= 0 ,0
Exp/Cntr=0.3,0.1

Type RM Length L Ch R = 1 ,19348.2 ,454.2,427.1,399.8
XS GIS Cut Line= 3
     1880886.741      570066.196     1880156.471      569816.617
     1879775.076      569784.135
#Sta/Elev= 30
       0  765.68    58.6  752.22   107.5  742.31   195.4  729.91     254  724.68
   293.1  720.07   371.2  706.78   449.4  691.65   468.9  689.66   556.8  685.23
   575.7  683.44   586.1  682.19   595.9  682.38  600.74  683.54   605.7  684.69
     635  696.17   654.5  702.22   703.4  715.48   742.4  724.79     762  728.79
   801.2  732.62   830.6  741.97   860.1  748.84   899.3  755.48   948.4  761.31
   987.7  769.54  1046.6  786.26    1076  795.44  1115.3  808.86  1154.5  823.41
#Mann= 3 , 0 , 0
       0     .08       0   575.7    .045       0  600.74     .08       0
Bank Sta=575.7,600.74
XS Rating Curve= 0 ,0
Exp/Cntr=0.3,0.1

Type RM Length L Ch R = 1 ,18921   ,421.3,431.2,441.2
XS GIS Cut Line= 3
     1880799.503      569284.209     1880119.301      569651.046
     1879767.809      569691.906
#Sta/Elev= 30
       0  825.51    68.5  828.75     137  830.83   146.7  830.45   156.5  829.04
   166.3  826.39   244.6  801.64   264.1  794.15   293.5  780.47   332.6  763.28
   342.4  758.39   430.4   710.5   440.2  705.42     450  701.15   469.6  695.65
   528.2  682.14     538  680.45   547.8  680.08     565  682.82   596.7  686.21
   645.6  692.72   684.8  701.74   733.7  711.59   792.5  719.95     822  725.96
   861.3  736.47   939.9  761.56  1018.6  785.51  1067.7  801.83  1126.7   822.8
#Mann= 3 , 0 , 0
       0      .1       0   528.2    .045       0     565     .06       0
Bank Sta=528.2,565
XS Rating Curve= 0 ,0
Exp/Cntr=0.3,0.1

Type RM Length L Ch R = 1 ,18489.7 ,484.6,484.8,485.1
XS GIS Cut Line= 3
     1880729.322      569107.183     1880322.042      569123.921
     1879551.629      569245.565
#Sta/Elev= 30
       0  749.31    67.9  743.56   126.2  735.65   184.4  732.06   271.8  730.66
   310.6  733.12     330  731.39   427.1  713.06   446.6  706.44   485.6  690.17
   531.8  678.78   544.1  677.86   561.8   679.3   670.9  681.19   680.6  682.22
   748.9  697.46   836.6   730.9   875.6  743.44   914.6  753.58   953.6  761.47
   982.8  765.78  1002.3  765.74  1031.6   759.9  1041.3  760.27  1060.8  763.91
  1080.3  765.04  1109.6   769.2  1129.1  772.54  1148.6   778.4  1187.6  796.83
#Mann= 3 , 0 , 0
       0     .08       0   531.8    .045       0   561.8     .08       0
Bank Sta=531.8,561.8
XS Rating Curve= 0 ,0
Exp/Cntr=0.3,0.1

Type RM Length L Ch R = 1 ,18004.6 ,461.8,457.4,453.1
XS GIS Cut Line= 3
     1880653.184      568633.965     1880271.357       568684.65
     1879487.427      568796.157
#Sta/Elev= 30
       0   826.7    38.5   823.7    86.7  818.18   125.2  811.92   154.1  803.88
   231.1  778.95   269.6   765.5   298.5  753.34   365.9  722.44   424.3  694.23
     434  690.17   443.8  687.45   463.4     685   492.7  682.63   551.4  680.36
   619.8  676.72   639.3  675.86   649.1  676.63   658.9  679.32   668.7  682.81
   678.4   685.3     698   689.2   707.8  692.21   717.6   695.9   737.1  704.22
     786  726.28   883.7  765.46   952.2  791.17  1020.6  813.48    1177  866.37
#Mann= 3 , 0 , 0
       0     .06       0   619.8    .045       0   649.1      .1       0
Bank Sta=619.8,649.1
XS Rating Curve= 0 ,0
Exp/Cntr=0.3,0.1

Type RM Length L Ch R = 1 ,17547.1 ,365.1,361,357
XS GIS Cut Line= 4
     1880504.508      568204.831     1880162.328      568222.621
     1879798.477       568334.26     1879497.564      568458.257
#Sta/Elev= 30
       0  857.52      49  846.86    88.1  839.91   107.7  834.81   117.5  831.36
   137.1  822.54   166.4   807.1   205.6  787.84   264.3  761.35   313.3  741.36
   352.4  729.02   371.9  721.84   430.5  698.56   459.8  685.69   485.9  675.43
     489   674.3   498.8  672.55   515.9  673.73   537.8  675.83   645.2  682.13
   674.4  686.51   684.2   688.5     694  691.37   713.5  699.88   761.5  723.53
   790.2  736.13   905.1  788.82   962.5  812.24  1010.4  829.39  1048.7  844.16
#Mann= 3 , 0 , 0
       0     .08       0   485.9    .045       0   515.9     .06       0
Bank Sta=485.9,515.9
XS Rating Curve= 0 ,0
Exp/Cntr=0.3,0.1

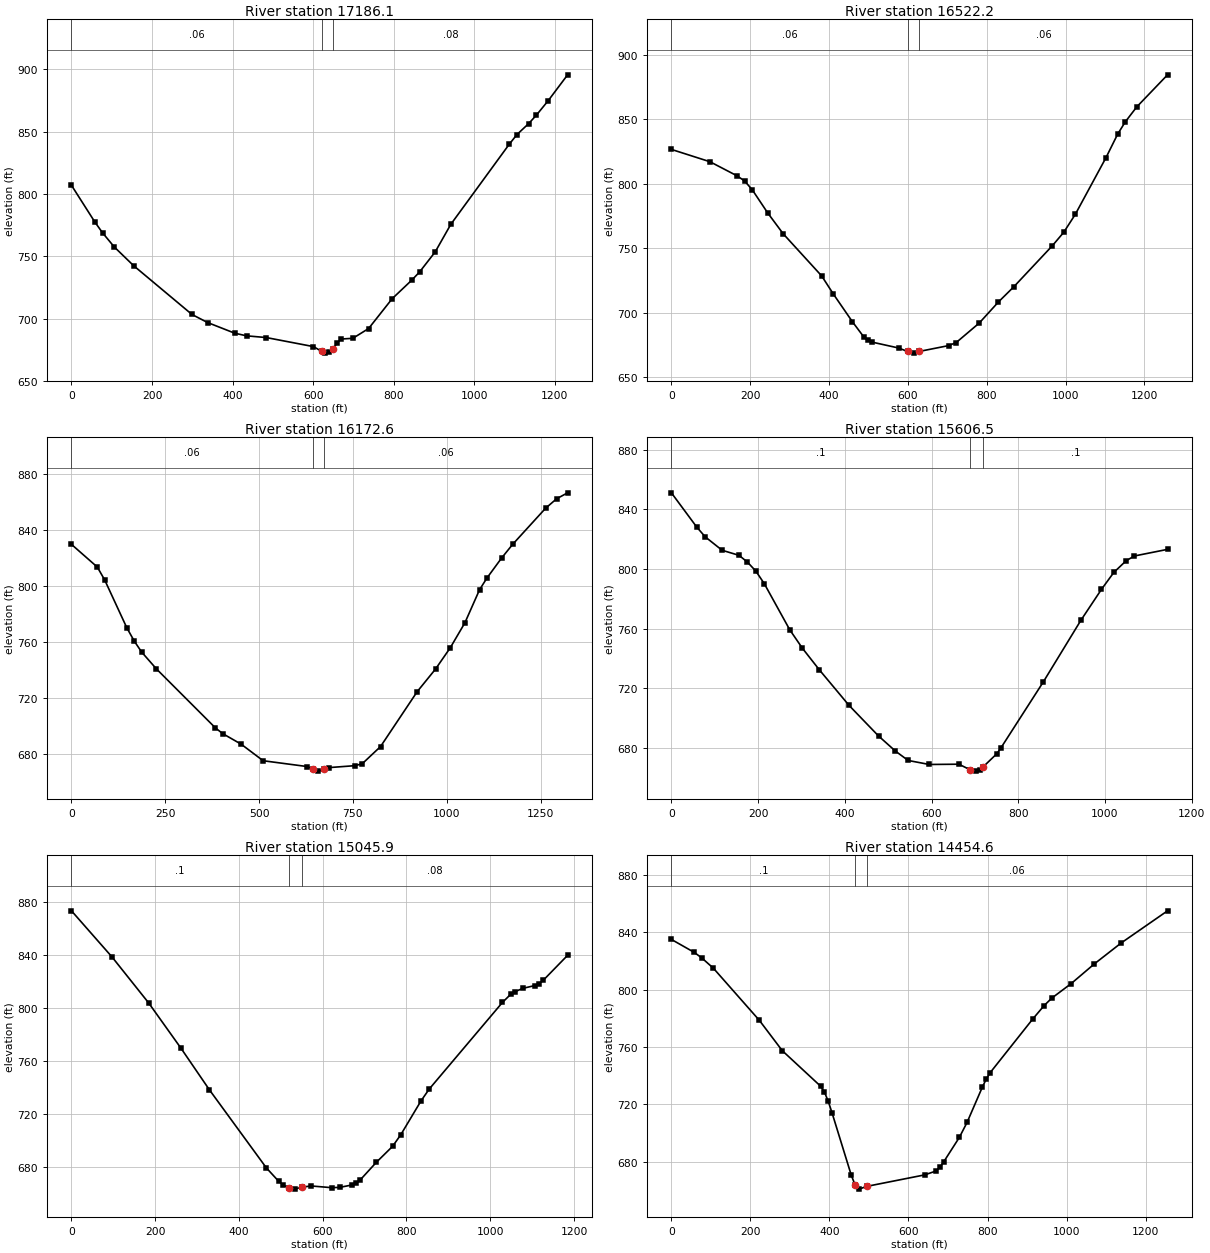
Type RM Length L Ch R = 1 ,17186.1 ,691.7,663.8,635
XS GIS Cut Line= 4
     1880186.037      567538.323     1880016.265      567906.605
     1879626.255      568087.882     1879302.913      568317.368
#Sta/Elev= 30
       0  806.92    57.9  777.54    77.2  768.78   106.2  757.47   154.5  742.36
   299.3  703.25   337.9   696.8   405.5  688.22   434.8  686.11   483.7  684.73
     601  677.47   621.8  673.54   630.3  672.23   640.1  672.83   649.9   675.9
   659.7  680.26   669.4  683.53   698.8  684.13   737.9  691.97   796.5  715.94
   845.3  730.86   864.6   737.4   903.3  753.48     942  775.56    1087   839.8
  1106.4  847.68  1135.4  856.44  1154.8  863.31  1183.8  874.79  1232.1  895.58
#Mann= 3 , 0 , 0
       0     .06       0   621.8    .045       0   649.9     .08       0
Bank Sta=621.8,649.9
XS Rating Curve= 0 ,0
Exp/Cntr=0.3,0.1

Type RM Length L Ch R = 1 ,16522.2 ,420.8,349.1,391.5
XS GIS Cut Line= 3
     1879710.442      567113.413     1879450.258      567431.039
      1879223.04      568248.026
#Sta/Elev= 30
       0  826.71    97.8  817.16   166.2  806.29   185.7  802.26   205.3  795.34
   244.4  777.43   283.5  761.34   381.3   728.6   410.6   714.7   459.3  693.06
   488.6  681.12   498.3  678.66   508.1  677.38   576.3  672.76     599  670.09
   615.3  668.78     629  670.11     703   674.6   722.5  676.98     781  692.12
   829.7  708.47   868.7  720.23   966.2  751.97   995.4  762.49  1024.6  776.36
  1102.6   820.4  1131.9  838.45  1151.4  848.07  1180.6  859.69  1258.6  884.53
#Mann= 3 , 0 , 0
       0     .06       0     599    .045       0     629     .06       0
Bank Sta=599,629
XS Rating Curve= 0 ,0
Exp/Cntr=0.3,0.1

Type RM Length L Ch R = 1 ,16172.6 ,577.1,566.3,555.5
XS GIS Cut Line= 3
     1879007.609       566917.43      1879038.02      567319.532
     1879115.138       568235.14
#Sta/Elev= 30
       0  829.79    68.8  813.59    88.5  804.38   147.5  770.15   167.2  760.71
   186.9  752.85   226.2  740.82   383.6  698.58   403.2  694.47   452.1  686.97
   510.8  675.12   628.1  670.96   643.1  669.31   657.4  667.69   673.1  668.88
   686.7  670.22   755.2  671.59   774.7  672.94   823.6  685.25   921.3  724.52
   970.2  740.69  1009.3  755.82  1048.4  773.73  1087.5  797.41    1107  805.68
  1146.2  820.03  1175.5  829.76  1263.4  855.62  1292.8   862.4  1322.1  866.65
#Mann= 3 , 0 , 0
       0     .06       0   643.1    .045       0   673.1     .06       0
Bank Sta=643.1,673.1
XS Rating Curve= 0 ,0
Exp/Cntr=0.3,0.1

Type RM Length L Ch R = 1 ,15606.5 ,547.7,559.9,571.7
XS GIS Cut Line= 3
     1878429.799       567191.13     1878811.626      567991.954
     1878919.755      568225.105
#Sta/Elev= 30
       0  851.03    58.5  828.05      78  821.52     117  812.52     156  809.13
   175.5  804.55     195  798.47   214.5  789.99     273  759.21   302.2  746.82
   341.2  732.38   409.5   708.6   477.7  688.04   516.7   677.9     546  671.63
   594.7  668.94     663  669.12   689.7  665.29     702  664.48   711.7  665.43
   719.7  667.57   750.7  676.19   760.4  680.25     858  724.42   944.3  765.55
   991.9  786.36  1020.4  797.71    1049  805.57    1068  808.71  1144.2  813.13
#Mann= 3 , 0 , 0
       0      .1       0   689.7    .045       0   719.7      .1       0
Bank Sta=689.7,719.7
XS Rating Curve= 0 ,0
Exp/Cntr=0.3,0.1

Type RM Length L Ch R = 1 ,15045.9 ,592.8,591.2,589.6
XS GIS Cut Line= 3
     1878169.615      567285.742     1878206.784      567691.223
     1878233.817      568468.394
#Sta/Elev= 30
       0  873.68      97  838.66   184.2  803.96   261.8  769.47   329.6     738
   465.5  678.92   494.7  668.85   504.4   666.3   519.5  663.56   533.6  662.86
   549.5  664.34   572.4  665.26     621  663.97   640.5  664.18   669.6     666
   679.4   667.4   689.1  669.68     728  683.16   766.8  695.27   786.3     704
   834.9  729.79   854.3  738.65  1029.3  804.33  1048.7  810.38  1058.5  812.31
  1077.9  814.96  1107.1  817.11  1116.8   818.5  1126.5  821.01  1184.8  839.98
#Mann= 3 , 0 , 0
       0      .1       0   519.5    .045       0   549.5     .08       0
Bank Sta=519.5,549.5
XS Rating Curve= 0 ,0
Exp/Cntr=0.3,0.1

Type RM Length L Ch R = 1 ,14454.6 ,318.9,336.8,354.6
XS GIS Cut Line= 3
     1877726.966      567353.322     1877618.838      567725.013
     1877696.555      568590.038
#Sta/Elev= 30
       0  834.91    58.1  825.84    77.4   821.9   106.4  814.81   222.6  778.53
   280.6   757.4   377.4   732.7   387.1  728.68   396.9  722.14   406.6  714.04
   455.4  670.47   465.2  663.66   474.9  660.93   494.4  662.85   640.8  670.84
   670.1  673.59   679.8  676.26   689.6  680.13   728.6  696.92   748.2  707.38
   787.2  732.18     797  737.69   806.7  742.07   914.1  779.33   943.3  788.82
   962.8  794.05  1011.6   804.1  1070.2  817.82  1138.5  832.49  1255.6  854.84
#Mann= 3 , 0 , 0
       0      .1       0   465.2    .045       0   494.4     .06       0
Bank Sta=465.2,494.4
XS Rating Curve= 0 ,0
Exp/Cntr=0.3,0.1