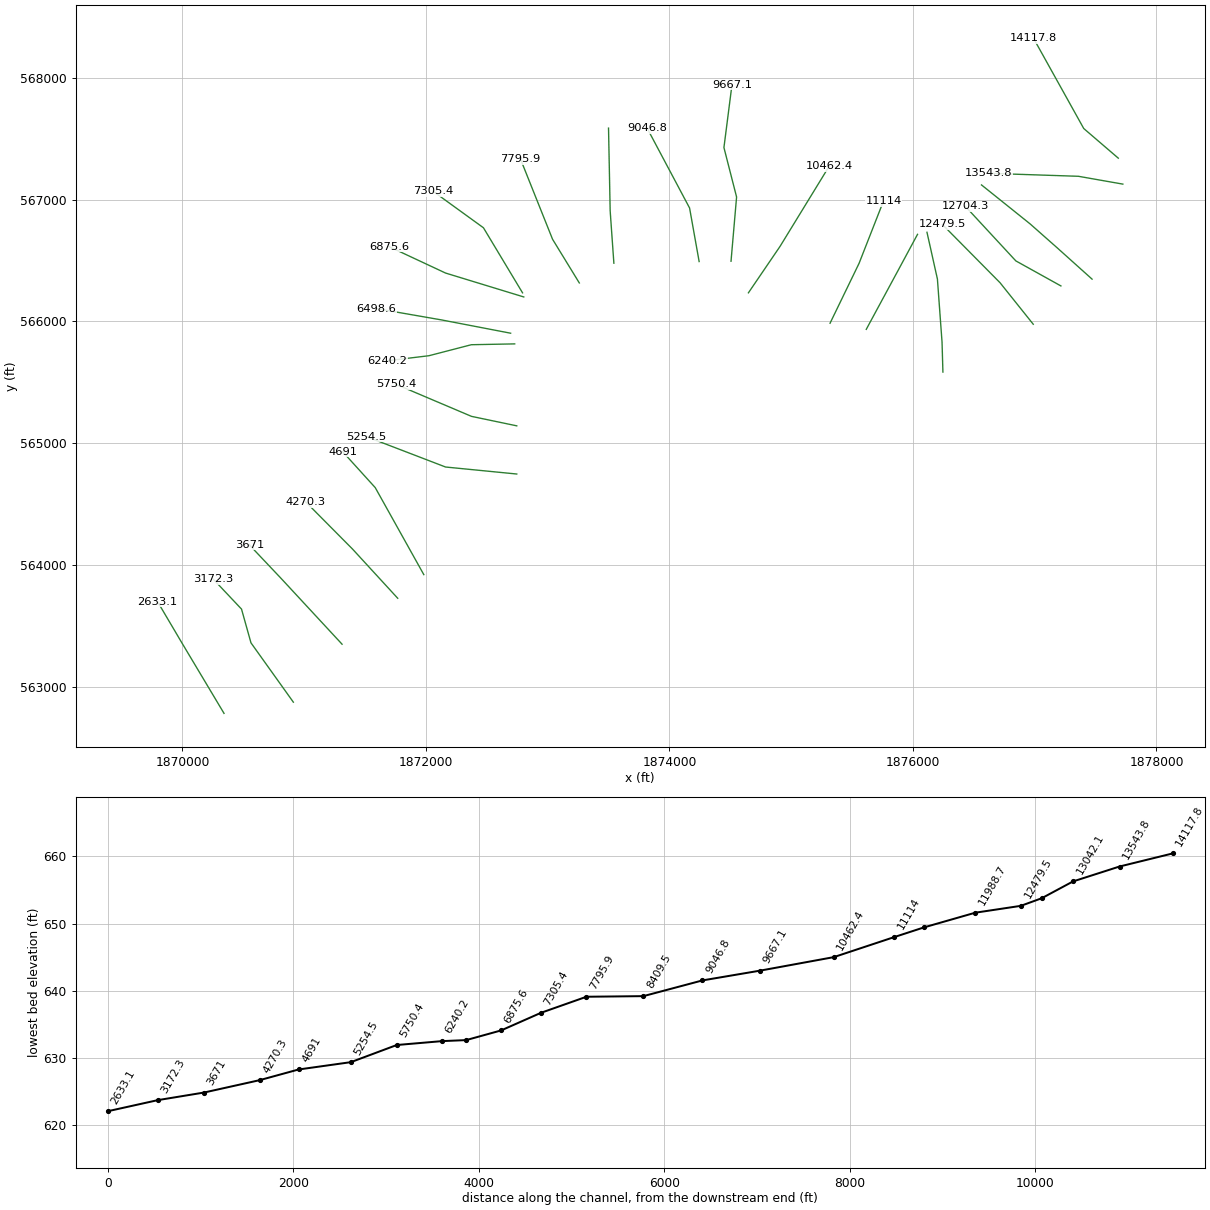
HEC-RAS study HurrcneCrk.prj: HurrcneCrk

--- HurrcneCrk.g01 (geometry) --- (continued)

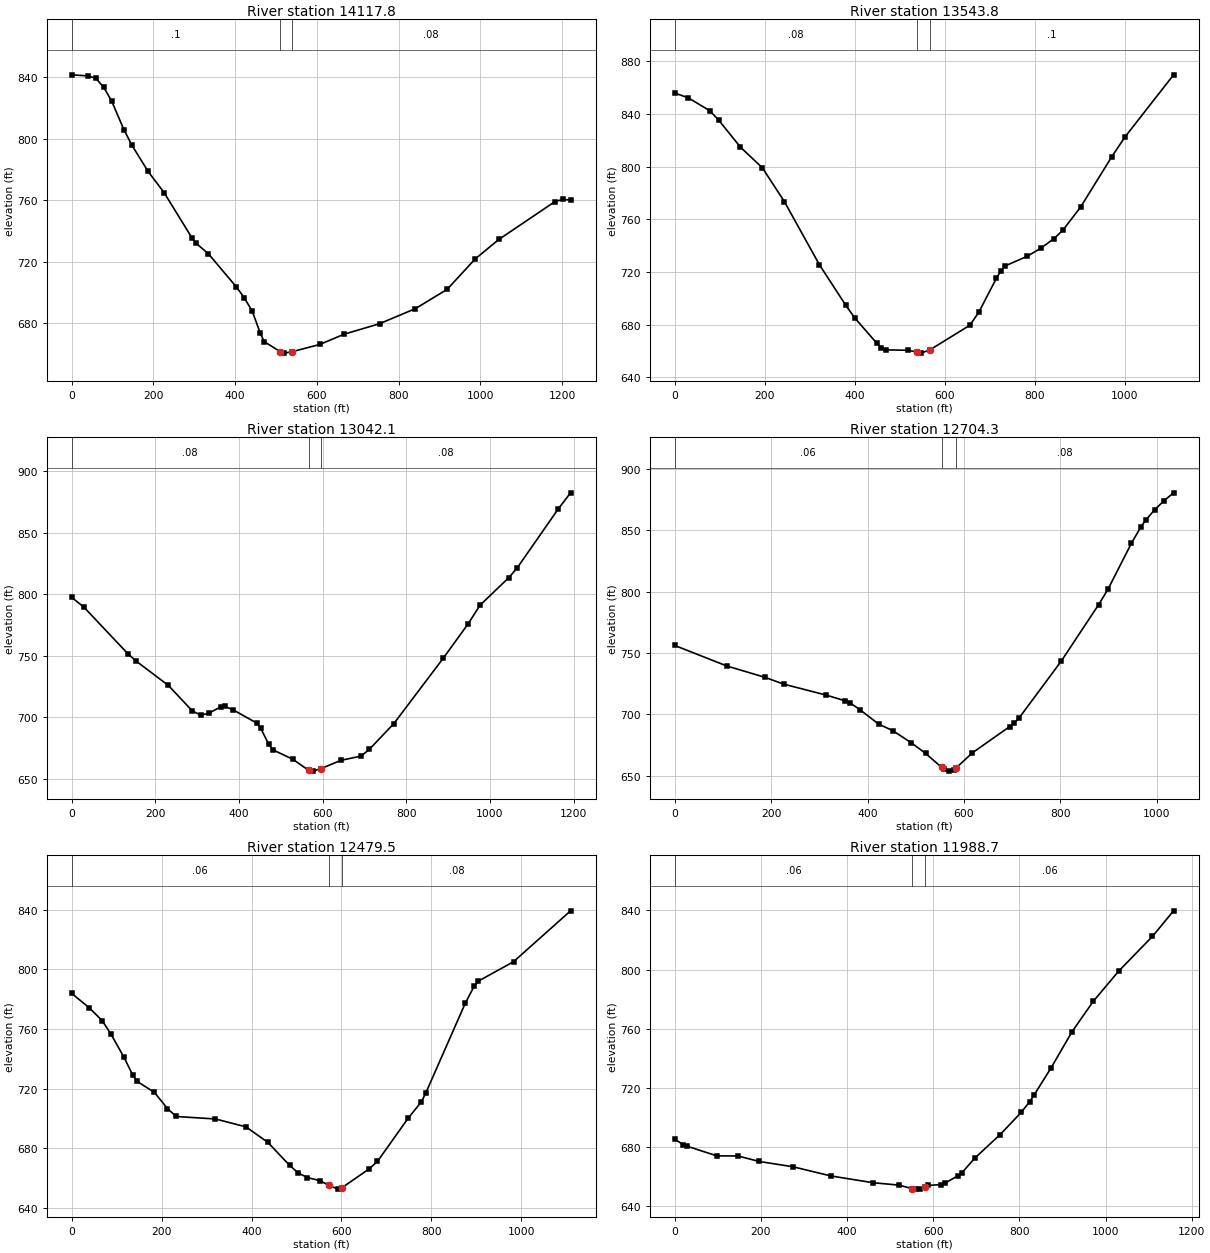
Type RM Length L Ch R = 1 ,14117.8 ,542.9,573.9,605
XS GIS Cut Line= 3
     1877686.418      567339.806     1877402.581      567583.094
     1876990.343      568323.097
#Sta/Elev= 30
       0  841.45    39.4  840.78      59  839.25    78.7  833.32    98.4  824.13
   127.9   805.8   147.6  795.64   186.9  778.69   226.3  764.84   295.1   735.1
     305  731.78   334.5  725.12     403  703.53   422.5  696.43     442  687.71
   461.5  673.47   471.2  667.92   510.2  661.44   519.9  660.43   539.4  661.34
   607.5  666.09   665.9  672.66   753.6  679.58   841.2  689.37   919.1  701.93
   987.2  721.62  1045.7  734.42    1182  758.86  1201.4  760.45  1220.9     760
#Mann= 3 , 0 , 0
       0      .1       0   510.2    .045       0   539.4     .08       0
Bank Sta=510.2,539.4
XS Rating Curve= 0 ,0
Exp/Cntr=0.3,0.1

Type RM Length L Ch R = 1 ,13543.8 ,523,501.6,480.3
XS GIS Cut Line= 3
     1877723.587      567126.929     1877358.654       567191.13
     1876621.169      567215.573
#Sta/Elev= 30
       0  855.67    29.2   852.3      78  842.34    97.5  835.33   146.3  814.67
     195  798.98   243.8  773.41   321.8  725.42   380.4  694.65     400  685.25
   449.2  665.92   459.1   662.6   468.9  660.95   518.1  660.64   537.8  659.36
   547.6  658.48   567.3  661.01   655.8  679.62   675.5  689.33   714.9  715.31
   724.7  720.87   734.6  724.66   783.8  732.03   813.3  738.02   842.8  745.32
   862.5  751.72   901.8  769.23   970.7  807.21  1000.2   822.3  1108.4  869.54
#Mann= 3 , 0 , 0
       0     .08       0   537.8    .045       0   567.3      .1       0
Bank Sta=537.8,567.3
XS Rating Curve= 0 ,0
Exp/Cntr=0.3,0.1

Type RM Length L Ch R = 1 ,13042.1 ,340.8,337.8,334.8
XS GIS Cut Line= 4
      1877470.95      566347.273     1877176.977      566610.835
     1876961.565      566800.904     1876562.984      567120.209
#Sta/Elev= 30
       0  797.49    28.9  789.71   134.8  751.56   154.1  745.73   231.1  725.98
   288.9  705.08   308.2  701.88   327.4   703.2   356.3   708.5   365.9  708.84
   385.2  706.27   442.7  695.28   452.3  690.94   471.4  677.94     481   673.6
   528.9  665.87   566.7  656.93   576.8  656.26   596.7  658.39   643.8  665.02
   691.9  668.48   711.6  673.92   770.5  694.95   888.4     748   947.3  775.66
   976.7  791.22  1045.5  813.63  1065.1  821.39  1163.3  869.32  1192.8  882.46
#Mann= 3 , 0 , 0
       0     .08       0   566.7    .045       0   596.7     .08       0
Bank Sta=566.7,596.7
XS Rating Curve= 0 ,0
Exp/Cntr=0.3,0.1

Type RM Length L Ch R = 1 ,12704.3 ,223.8,224.8,225.8
XS GIS Cut Line= 3
      1877214.99      566291.519     1876844.989      566496.794
     1876429.372      566945.357
#Sta/Elev= 30
       0  756.24   108.2  739.47     187  730.26   226.3  724.67   314.9  715.66
   354.2  710.98   364.1  709.28   383.8  703.97   423.1  692.08   452.2  686.79
   491.1  676.79   520.2  668.26  553.72  656.82     559  655.23   568.7  653.76
   578.4  654.62  582.89  656.06   617.3  668.64   694.9   690.1   704.6  693.19
   714.3   697.1   801.7  743.43   879.3  789.54   898.8   802.2   947.3  839.61
   966.7  852.74   976.4  858.19   995.8  867.01  1015.2  874.34  1034.6  880.63
#Mann= 3 , 0 , 0
       0     .06       0  553.72    .045       0  582.89     .08       0
Bank Sta=553.72,582.89
XS Rating Curve= 0 ,0
Exp/Cntr=0.3,0.1

Type RM Length L Ch R = 1 ,12479.5 ,513.9,491.1,468.4
XS GIS Cut Line= 3
     1876987.823       565977.18     1876715.241      566317.627
      1876241.54      566796.106
#Sta/Elev= 30
       0   783.9    38.8  774.32    67.8  765.64    87.2  756.68   116.3  741.11
   135.7  729.19   145.4  724.92   184.1  717.46   213.2  706.63   232.6  701.32
   319.8  699.66   387.7  694.37   436.1  684.05   484.9  668.52   504.4  663.38
     524  660.41   553.2  658.23   571.5  655.16   592.2  652.63   601.5  653.66
   660.6  665.98   680.1  671.23   748.4  700.23   777.6  711.12   787.4     717
   875.2   777.2   894.8  788.54   904.5  792.11   982.6  805.07  1109.4   839.2
#Mann= 3 , 0 , 0
       0     .06       0   571.5    .045       0   601.5     .08       0
Bank Sta=571.5,601.5
XS Rating Curve= 0 ,0
Exp/Cntr=0.3,0.1

Type RM Length L Ch R = 1 ,11988.7 ,572.6,554.2,534.6
XS GIS Cut Line= 4
     1876246.021      565584.661     1876238.884      565829.685
     1876200.822      566348.282      1876115.18      566731.585
#Sta/Elev= 30
       0  685.32    19.6  681.77    29.4  680.57      98   674.1   147.1  674.02
   196.1  670.32   274.6  666.72   362.9   660.5     461  655.92   519.8  654.35
   551.4  651.95   559.1  651.61   568.9  651.86   581.4  653.19   588.5   654.1
     618  654.69   627.8  655.72   657.2  660.62     667  662.76   696.4  672.52
   755.3  688.47   804.4  703.51     824  710.74   833.8  715.04   873.1  733.34
   922.2  757.98   971.3  778.48  1030.2  798.89  1108.8  822.43  1157.9  839.74
#Mann= 3 , 0 , 0
       0     .06       0   551.4    .045       0   581.4     .06       0
Bank Sta=551.4,581.4
XS Rating Curve= 0 ,0
Exp/Cntr=0.3,0.1

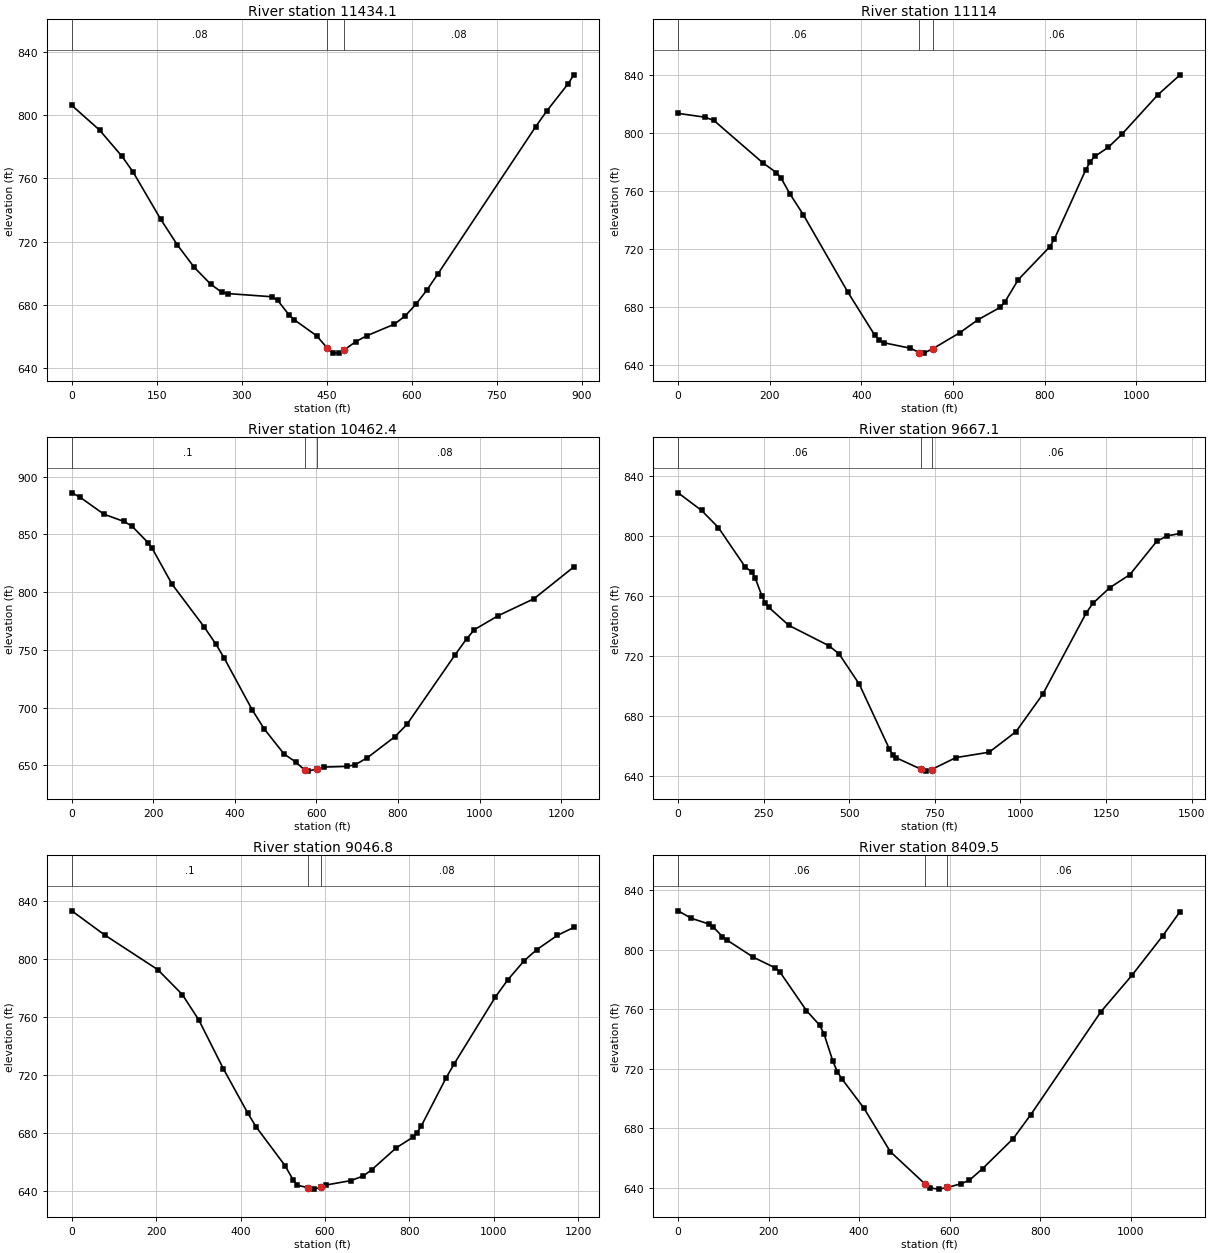
Type RM Length L Ch R = 1 ,11434.1 ,318.6,320.1,323.8
XS GIS Cut Line= 3
     1875616.582      565935.321      1875882.73      566427.575
     1876037.463       566714.69
#Sta/Elev= 30
       0  806.28    49.1   790.6    88.4   774.1     108  764.18   157.1  734.08
   186.5  717.85     216  703.77   245.4  692.99   265.1  687.86   274.9  687.14
   353.4   685.1   363.2  682.91   382.9  673.82   392.7  670.53     432  660.43
   451.1  652.53   461.4  649.54   471.2  649.42   481.1  651.57   500.7  656.57
   520.3  660.37   569.2  667.73   588.4  672.98   607.6  680.47   626.8  689.42
   645.9  699.46   818.6  792.74   837.8  802.52   876.2  820.07   885.8   825.6
#Mann= 3 , 0 , 0
       0     .08       0   451.1    .045       0   481.1     .08       0
Bank Sta=451.1,481.1
XS Rating Curve= 0 ,0
Exp/Cntr=0.3,0.1

Type RM Length L Ch R = 1 ,11114   ,653.7,651.5,646.9
XS GIS Cut Line= 3
     1875319.181        565985.6     1875557.426      566476.884
     1875758.089      566988.162
#Sta/Elev= 30
       0  813.47    58.5  810.84      78   808.6   185.2  779.22   214.5  772.59
   224.2  769.06   243.8  757.98     273  743.61   370.5  689.97     429  660.35
   438.8  656.94   448.5  655.17     507  651.34   526.5   648.3   536.2  647.98
   555.8  651.04   614.7  662.08   653.9  670.97   702.9  679.59   712.7  683.24
   742.2  698.71   810.8  721.36   820.6  726.49   889.3  774.47   899.1  780.12
   908.9  783.73   938.3  789.97   967.8  798.91  1046.2  826.12  1095.2  840.08
#Mann= 3 , 0 , 0
       0     .06       0   526.5    .045       0   555.8     .06       0
Bank Sta=526.5,555.8
XS Rating Curve= 0 ,0
Exp/Cntr=0.3,0.1

Type RM Length L Ch R = 1 ,10462.4 ,771.2,794.9,818.6
XS GIS Cut Line= 3
     1874648.692      566234.871     1874908.875      566616.699
     1875310.977      567272.226
#Sta/Elev= 30
       0  885.87    19.7  882.24    78.6   867.4   127.8   861.1   147.5  857.14
   186.8  842.81   196.6  838.24   245.8  806.88   324.4  769.96   353.9  754.67
   373.6  743.01   442.4   698.1   471.8  681.62   520.4  659.92   549.7  652.77
   571.1  645.96   578.9     645   601.1  646.84   617.8  648.49   676.2  649.12
   695.7  650.62   724.9  656.61     793  674.92   822.2  685.54     939  745.09
   968.2  759.47   987.7  767.51  1046.1  779.57  1133.7  794.22  1231.1  821.68
#Mann= 3 , 0 , 0
       0      .1       0   571.1    .045       0   601.1     .08       0
Bank Sta=571.1,601.1
XS Rating Curve= 0 ,0
Exp/Cntr=0.3,0.1

Type RM Length L Ch R = 1 ,9667.1  ,613.4,619.8,625.8
XS GIS Cut Line= 4
     1874505.873       566494.26     1874551.489      567021.384
     1874447.585      567426.865     1874513.532      567941.269
#Sta/Elev= 30
       0  828.51    68.6  816.74   117.6  805.36     196  779.08   215.6  775.74
   225.4  771.56     245   759.6   254.8  755.01   264.6  752.21   323.3  740.18
   440.9  726.53   470.3  721.09   529.1  700.96   616.7  657.97   626.4  654.03
   636.2  651.96   710.4  644.18   723.8  642.99   740.4  644.07   811.4     652
   908.7  655.62   986.8  669.26  1065.1  694.25  1192.3  748.52  1211.9  754.92
  1260.8  765.26  1319.5  773.96  1397.8   796.1  1427.2  799.73  1466.3  801.43
#Mann= 3 , 0 , 0
       0     .06       0   710.4    .045       0   740.4     .06       0
Bank Sta=710.4,740.4
XS Rating Curve= 0 ,0
Exp/Cntr=0.3,0.1

Type RM Length L Ch R = 1 ,9046.8  ,651.9,637.3,623.3
XS GIS Cut Line= 3
     1874244.003      566491.463     1874165.494      566930.946
     1873816.556      567586.523
#Sta/Elev= 30
       0  833.36    77.6  816.78   203.8  792.81     262  775.62   300.9  758.16
   359.1  724.52   417.3  693.73   436.7  684.45   505.1  657.77   524.6  647.81
   534.4  644.25   559.5  642.51   573.5  641.54   589.5  642.73   602.8   644.4
   661.4  647.43   690.7  650.64   710.3  654.82   768.9  670.06     808   677.3
   817.8   680.4   827.5  684.81   886.2  717.92   905.7  727.82  1003.4  773.92
  1032.8  785.78  1071.8  799.01  1101.2  806.52    1150  816.39  1189.1  821.92
#Mann= 3 , 0 , 0
       0      .1       0   559.5    .045       0   589.5     .08       0
Bank Sta=559.5,589.5
XS Rating Curve= 0 ,0
Exp/Cntr=0.3,0.1

Type RM Length L Ch R = 1 ,8409.5  ,603.8,613.5,624.2
XS GIS Cut Line= 3
     1873543.757       566478.16     1873513.346      566907.293
      1873499.83      567586.474
#Sta/Elev= 30
       0  826.01    29.3  820.97    68.4  817.14    78.2  814.99    97.8  808.75
   107.6  806.45   166.2  794.88   215.1  787.65   224.9  784.99   283.6  759.07
   312.9  749.24   322.7   743.2   342.2  724.92     352  717.93   361.8  713.27
   410.6   693.6     469  664.35   546.7  642.38   556.4  640.02   575.8   639.2
   595.2  640.32   624.3  642.71   643.7  645.18   672.8   652.9   740.8  673.18
   779.6  689.23   934.8  758.41  1002.8  782.62  1070.7  809.06  1109.5  825.51
#Mann= 3 , 0 , 0
       0     .06       0   546.7    .045       0   595.2     .06       0
Bank Sta=546.7,595.2
XS Rating Curve= 0 ,0
Exp/Cntr=0.3,0.1

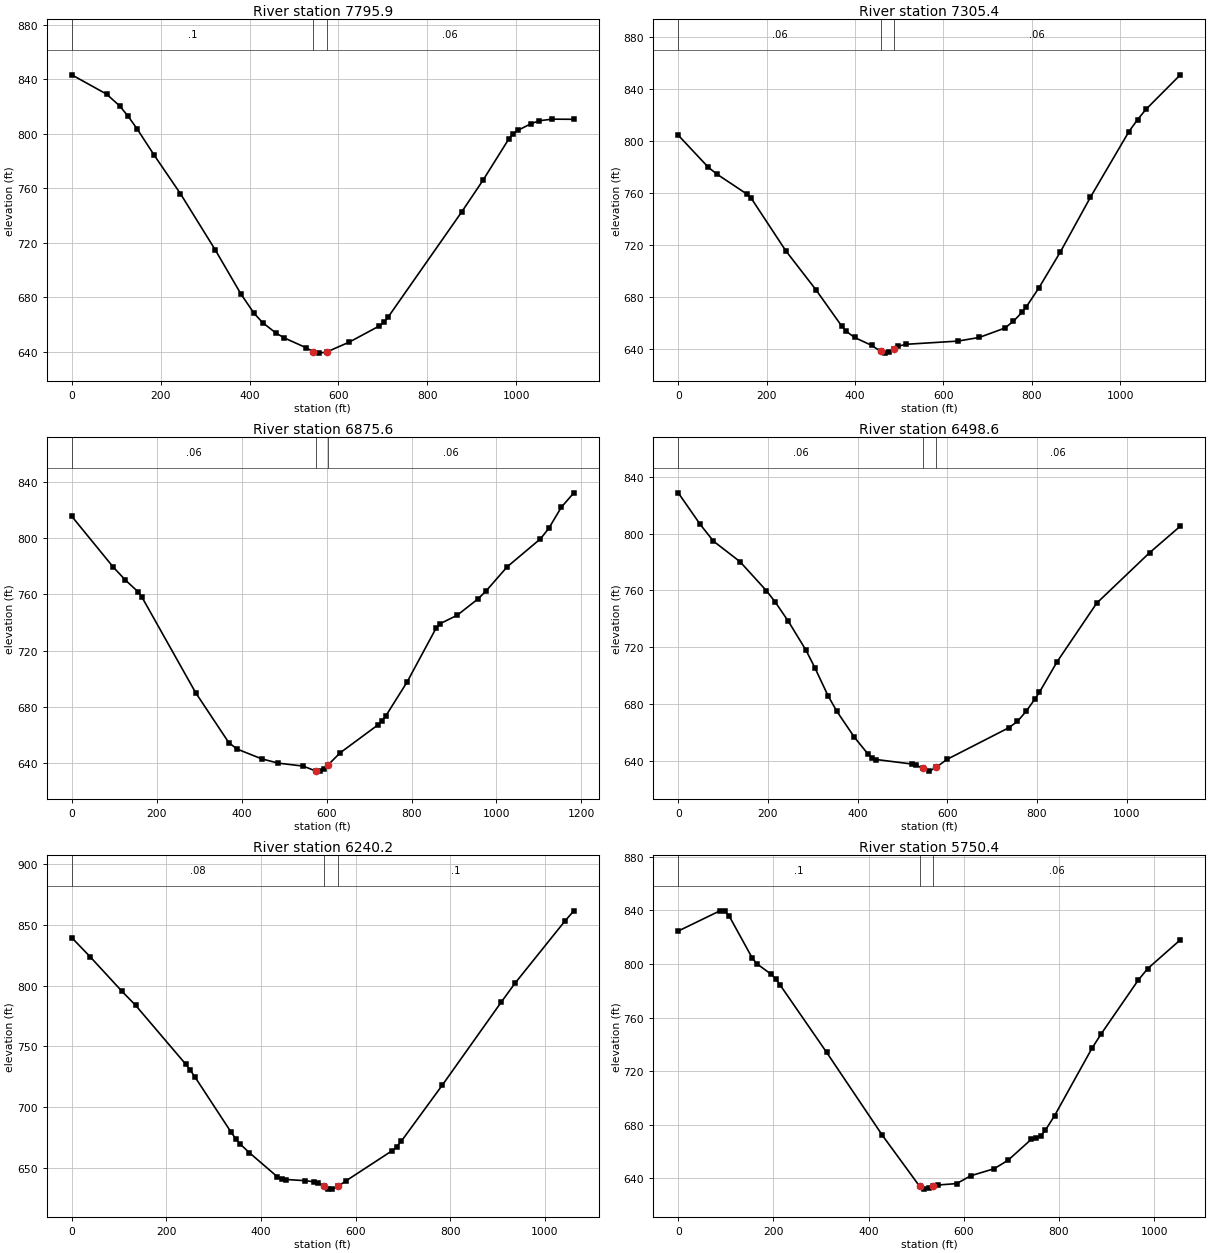
Type RM Length L Ch R = 1 ,7795.9  ,484.2,490.4,495.7
XS GIS Cut Line= 3
     1873259.921      566315.968     1873040.285      566674.142
     1872776.723      567333.048
#Sta/Elev= 30
       0  843.23    78.2   829.1   107.5  820.53     127  812.76   146.6   803.8
   185.6  784.24   244.3  756.16   322.4  715.09   381.1  682.25   410.4  668.22
   429.9  661.36     459  653.94   478.5  650.21   527.1  643.11   543.3  640.09
   556.2  639.11   573.3  639.91   624.3  647.17   692.4   659.1   702.1   661.6
   711.8   665.5   877.1  742.52   925.7  766.08     984  796.48   993.7  800.19
  1003.4  802.44  1032.6  807.25    1052  809.56  1081.2  810.72  1129.8  810.61
#Mann= 3 , 0 , 0
       0      .1       0   543.3    .045       0   573.3     .06       0
Bank Sta=543.3,573.3
XS Rating Curve= 0 ,0
Exp/Cntr=0.3,0.1

Type RM Length L Ch R = 1 ,7305.4  ,407.8,429.7,451.5
XS GIS Cut Line= 3
     1872793.618      566234.871     1872472.613      566768.754
     1872056.995      567069.486
#Sta/Elev= 30
       0  804.25    68.1  779.55    87.6  774.29   155.7  758.91   165.5  755.59
   243.3  715.42   311.5  685.44   369.9   657.5   379.6  653.64   399.1  648.74
     438  642.62   457.9  638.08   467.2  636.72     477  637.25   487.9  639.75
   496.4  641.98   515.9  643.52   632.6  645.96     681  648.76   739.1  655.99
   758.5  661.29   777.8  668.06   787.5  672.28   816.5  687.12   864.9  714.67
   932.7  756.61  1019.8  807.06  1039.2  816.19  1058.5  824.19    1136  850.65
#Mann= 3 , 0 , 0
       0     .06       0   457.9    .045       0   487.9     .06       0
Bank Sta=457.9,487.9
XS Rating Curve= 0 ,0
Exp/Cntr=0.3,0.1

Type RM Length L Ch R = 1 ,6875.6  ,373.8,377,380.4
XS GIS Cut Line= 3
     1872803.755      566201.081     1872161.744      566397.064
      1871698.82       566613.32
#Sta/Elev= 30
       0  815.62    97.3  779.56   126.5  770.12   155.6  761.99   165.4  757.94
   291.8  689.91   369.7  654.41   389.1  649.85   447.5   642.8   486.4  639.78
   544.8  637.69     574  634.22   583.7   634.1   593.4  635.42   603.2  638.46
   632.3  647.22   720.4   666.9   730.2  669.82     740   673.7   789.2  697.38
     858  736.04   867.8  739.22   907.1  745.05   956.2  756.68   975.9  762.55
    1025  779.57  1103.6  799.57  1123.2  807.04  1152.7  822.06  1182.2  832.34
#Mann= 3 , 0 , 0
       0     .06       0     574    .045       0   603.2     .06       0
Bank Sta=574,603.2
XS Rating Curve= 0 ,0
Exp/Cntr=0.3,0.1

Type RM Length L Ch R = 1 ,6498.6  ,245.2,258.6,271.8
XS GIS Cut Line= 3
     1872695.865      565903.532      1872126.47      566012.955
     1871594.329      566105.454
#Sta/Elev= 30
       0   828.8    49.1   806.5    78.6  794.72   137.6  780.32   196.6  759.85
   216.2   751.9   245.7  738.21     285  717.84   304.6  705.64   334.1  685.82
   353.8   674.8   393.1  656.46   422.6  644.96   432.4  642.24   442.2  640.82
   520.8  637.69   530.7     637   544.9  634.56   560.2  632.66   574.9  635.23
   599.4  640.92   736.9  663.16   756.6  667.71   776.2   674.9   795.9  683.59
   805.7  688.28     845  709.71   933.4  751.04  1051.2  786.55  1119.9   805.3
#Mann= 3 , 0 , 0
       0     .06       0   544.9    .045       0   574.9     .06       0
Bank Sta=544.9,574.9
XS Rating Curve= 0 ,0
Exp/Cntr=0.3,0.1

Type RM Length L Ch R = 1 ,6240.2  ,509.2,489.5,469.9
XS GIS Cut Line= 4
     1872729.417      565815.875     1872373.323      565809.105
     1872024.838      565718.778     1871681.925      565677.336
#Sta/Elev= 30
       0  839.41    38.5  823.84   105.9  795.37   134.8  783.83   240.6  735.46
   250.3  730.55   259.9  725.13   336.9  679.35   346.5  674.02   356.2  669.52
   375.6  662.46     434  642.89   443.7  641.04   453.5  640.42   492.4   639.5
   511.8  638.56   521.6  637.42     533  634.86     541  633.01   550.8  632.51
     563   634.7   579.9  639.34   677.2  664.07     687  667.48   696.7  671.89
   783.3  717.98     908  786.33   936.8  801.73  1042.4  852.93  1061.6   861.5
#Mann= 3 , 0 , 0
       0     .08       0     533    .045       0     563      .1       0
Bank Sta=533,563
XS Rating Curve= 0 ,0
Exp/Cntr=0.3,0.1

Type RM Length L Ch R = 1 ,5750.4  ,494,494.7,495.4
XS GIS Cut Line= 3
     1872746.312      565143.453     1872374.621       565221.17
     1871752.884      565484.732
#Sta/Elev= 30
       0  824.54    87.6  839.62    97.4  839.41   107.1   835.7   155.8  804.21
   165.5  800.04   194.7  792.43   204.5   788.9   214.2  784.22   311.6   734.1
   428.7  672.21     507  634.13   516.7  631.93   526.5  632.44   536.3     634
   546.1     635   585.2  636.07   614.6   641.9   663.6  647.12   692.9  653.42
   741.8  669.09   751.6  669.78   761.4  671.63   771.2  675.77   790.8  686.74
   869.1  736.88   888.6  747.72   966.9  788.05   986.5   796.5    1055  817.95
#Mann= 3 , 0 , 0
       0      .1       0     507    .045       0   536.3     .06       0
Bank Sta=507,536.3
XS Rating Curve= 0 ,0
Exp/Cntr=0.3,0.1

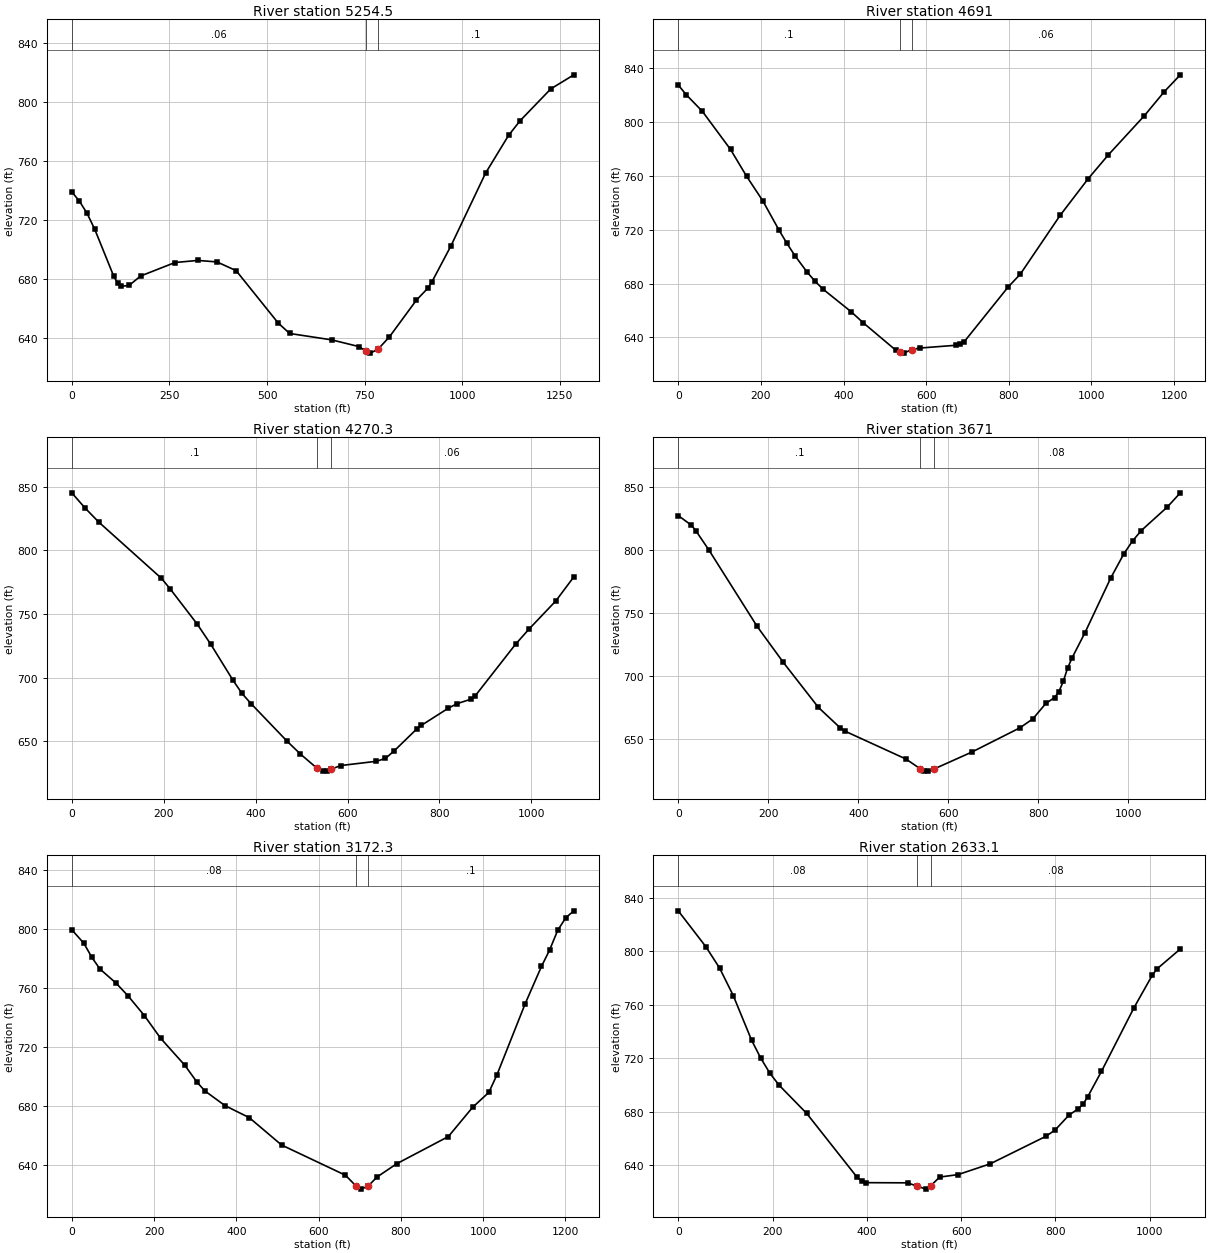
Type RM Length L Ch R = 1 ,5254.5  ,584.8,563.5,542.2
XS GIS Cut Line= 3
     1872746.312      564748.109     1872161.744      564805.552
     1871509.596      565055.599
#Sta/Elev= 30
       0  739.02    19.6  732.69    39.2  724.38    58.7  713.65   107.7  681.51
   117.5  677.09   127.3  674.83   146.8  675.39   176.2  681.79   264.3  690.97
   323.1   692.4     372  691.37     421  685.44   528.6  649.86     558  642.74
   666.1  638.37   734.9  633.86   754.6  630.65   764.4  629.38   784.1  631.97
   813.6  640.47   882.5  665.37     912  673.56   921.8  677.55     971  702.26
  1059.6  751.69  1118.6  777.37  1148.1  787.34  1226.8  809.01  1285.8  818.56
#Mann= 3 , 0 , 0
       0     .06       0   754.6    .045       0   784.1      .1       0
Bank Sta=754.6,784.1
XS Rating Curve= 0 ,0
Exp/Cntr=0.3,0.1

Type RM Length L Ch R = 1 ,4691    ,413.4,420.4,428.6
XS GIS Cut Line= 3
     1871982.858      563922.526     1871583.934      564636.602
     1871316.993      564930.575
#Sta/Elev= 30
       0   827.6    19.5  820.35    58.4  808.04   126.6  779.69   165.5  759.72
   204.5  741.59   243.4  719.98   262.9  709.96   282.4  700.71   311.6  688.63
   331.1  681.71   350.6  675.79   418.7  658.99   447.9  650.79   525.8  630.64
   535.6  628.82   545.3  628.29   564.8  630.84   584.2  632.06   671.9  634.12
   681.6  634.74   691.4  636.52   798.5  677.51   827.6  686.92   924.5  730.85
   992.3  758.05  1040.7  775.64  1127.9  804.76  1176.3  822.69    1215  835.19
#Mann= 3 , 0 , 0
       0      .1       0   535.6    .045       0   564.8     .06       0
Bank Sta=535.6,564.8
XS Rating Curve= 0 ,0
Exp/Cntr=0.3,0.1

Type RM Length L Ch R = 1 ,4270.3  ,599.3,599.4,598.3
XS GIS Cut Line= 3
     1871768.452      563728.711     1871399.062      564130.669
     1871013.961      564518.429
#Sta/Elev= 30
       0  845.17    29.2  833.14    58.5  822.28     195  778.09   214.5  769.57
     273  742.08   302.2  726.41   350.9  697.96   370.4  687.67   389.9  679.73
   467.9  650.39   497.2   640.2     533  629.14   545.9   626.7   555.7  626.81
     563  628.02     585  631.08     663  634.43   682.5   636.7     702  642.77
   750.8  659.87   760.6  662.61   819.2  676.09   838.7   679.7     868  683.12
   877.7  685.76   965.5  726.27   994.8  738.18  1053.4   760.4  1092.4  779.21
#Mann= 3 , 0 , 0
       0      .1       0     533    .045       0     563     .06       0
Bank Sta=533,563
XS Rating Curve= 0 ,0
Exp/Cntr=0.3,0.1

Type RM Length L Ch R = 1 ,3671    ,512.9,498.5,484.2
XS GIS Cut Line= 3
       1871311.5      563351.641     1870808.396      563894.115
     1870549.959       564166.92
#Sta/Elev= 30
       0  827.16    29.2  819.53    38.9  815.28    68.1  799.92   175.2  739.48
   233.6  710.87   311.5  675.27   360.2  659.02   369.9   656.6   506.2   634.4
     538  626.65   545.2   625.2   554.9  624.86     568  626.49   652.2  639.92
   759.1  659.11     788  666.25   816.9  678.47   836.2   683.1   845.8  687.75
   855.5  695.88   865.1  706.34   874.8   714.3   903.7  734.41   961.5   778.1
   990.4  797.04  1009.6  807.11  1028.9   815.3  1086.7  833.92  1115.6  845.16
#Mann= 3 , 0 , 0
       0      .1       0     538    .045       0     568     .08       0
Bank Sta=538,568
XS Rating Curve= 0 ,0
Exp/Cntr=0.3,0.1

Type RM Length L Ch R = 1 ,3172.3  ,531.7,539.1,546.5
XS GIS Cut Line= 4
     1870911.512       562876.14     1870563.475      563362.717
     1870485.758      563639.795     1870255.985      563883.084
#Sta/Elev= 30
       0  799.59    29.4  790.42      49  780.78    68.6  772.94   107.9  763.36
   137.3  754.59   176.5   741.4   215.8  726.08   274.6  707.79     304  696.43
   323.6  690.31   372.7  680.32   431.5   672.2     510  653.65   665.4  633.14
   690.6  625.97   703.8  623.73   720.6  625.83   742.1  631.94   790.1  640.97
   915.5  659.37   974.6  679.23    1014  689.33  1033.6  701.18  1102.5  749.58
  1141.9  774.73  1161.6  785.81  1181.3  799.17    1201  807.71  1220.6  812.42
#Mann= 3 , 0 , 0
       0     .08       0   690.6    .045       0   720.6      .1       0
Bank Sta=690.6,720.6
XS Rating Curve= 0 ,0
Exp/Cntr=0.3,0.1

Type RM Length L Ch R = 1 ,2633.1  ,530.6,532.9,535.2
XS GIS Cut Line= 3
     1870342.094      562784.112     1870002.504      563351.785
     1869797.229      563698.977
#Sta/Elev= 30
       0  830.28    58.4  803.52    87.6  787.54   116.7  766.87   155.6  733.47
   175.1     720   194.6  708.68     214   699.8   272.4  678.73   379.4  630.92
   389.1  627.99   398.8  626.92   486.4  626.78   505.5  624.43   525.3  622.08
   535.5  624.59   554.5   631.1   593.4  632.94   661.5  640.98   779.5  661.55
   799.2  666.26   828.7  677.45   848.4   682.2   858.2  685.48   868.1  690.95
   897.6  710.18   966.5  757.77  1005.8  782.38  1015.6  786.91  1064.8  801.73
#Mann= 3 , 0 , 0
       0     .08       0   505.5    .045       0   535.5     .08       0
Bank Sta=505.5,535.5
XS Rating Curve= 0 ,0
Exp/Cntr=0.3,0.1