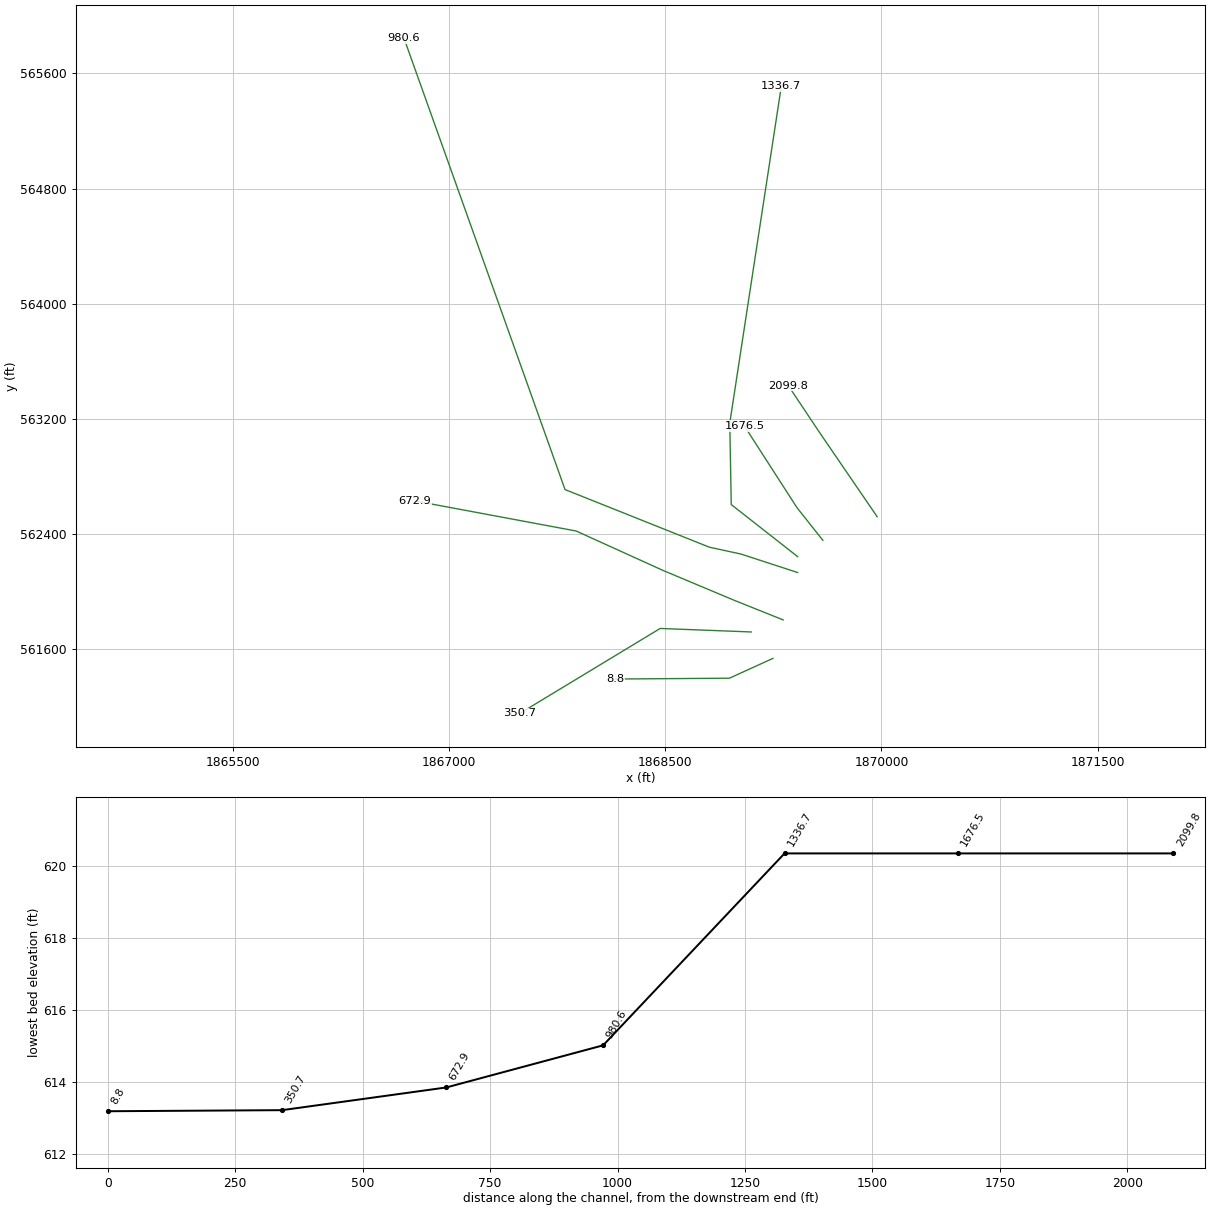
HEC-RAS study HurrcneCrk.prj: HurrcneCrk

--- HurrcneCrk.g01 (geometry) --- (continued)

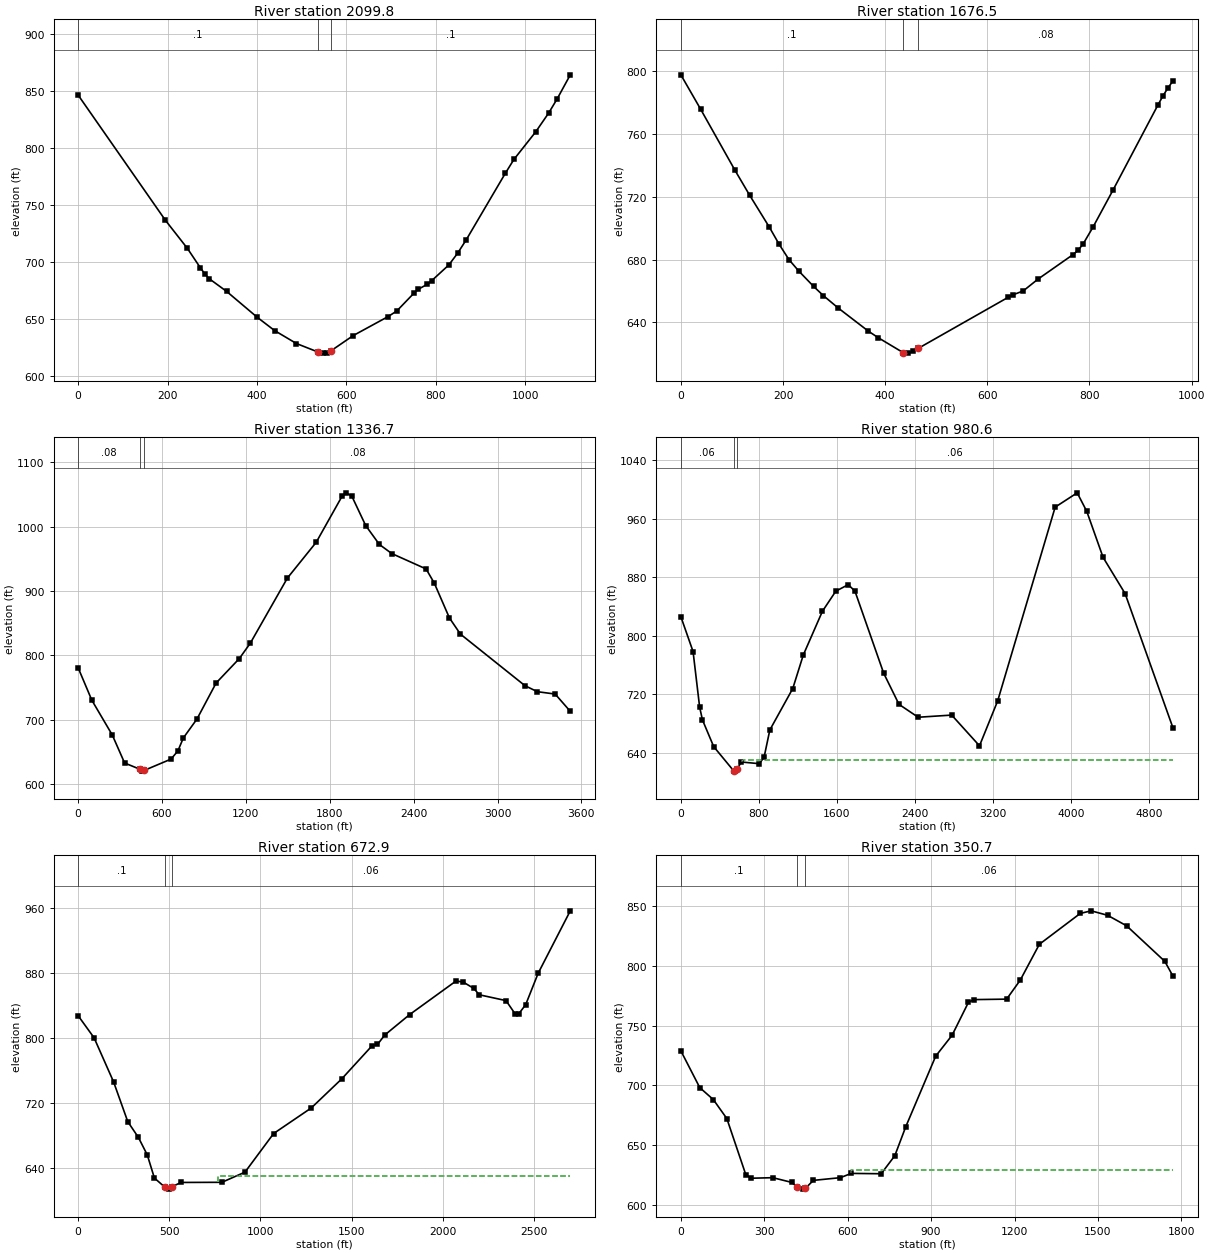
Type RM Length L Ch R = 1 ,2099.8  ,424.1,423.3,422.5
XS GIS Cut Line= 3
     1869970.346       562519.49     1869563.289       563116.05
     1869353.721      563430.938
#Sta/Elev= 30
       0  846.16   195.2  736.56     244  712.16   273.3  695.04     283  689.75
   292.8  685.54   331.8  674.43   400.1  651.83   439.2  640.11     488  628.78
   536.8  621.25   546.5  620.36   556.3  620.56     566  622.56   614.8  635.66
   692.9  652.32   712.4  657.21   751.3  673.02     761  676.36   780.4  680.54
   790.1   683.6   828.9  697.55   848.3  707.69   867.7   719.5     955  777.63
   974.4  789.89  1022.9  813.91    1052  830.42  1071.4   843.1  1100.4   863.9
#Mann= 3 , 0 , 0
       0      .1       0   536.8    .045       0     566      .1       0
Bank Sta=536.8,566
XS Rating Curve= 0 ,0
Exp/Cntr=0.3,0.1

Type RM Length L Ch R = 1 ,1676.5  ,329.2,339.6,349.9
XS GIS Cut Line= 3
       1869593.7      562355.773     1869414.613      562582.167
      1869049.68       563149.84
#Sta/Elev= 30
       0  797.77    38.5  775.98   105.8     737   134.7  720.99   173.2  700.68
   192.4  689.75   211.7  679.94   230.9  672.67   259.8  662.91     279  657.02
   308.2  649.08   366.9  634.41   386.5  630.17   435.4  620.65   445.2  620.36
   454.9   621.4   464.7  623.39   640.8  655.95   650.5  657.58   670.1  659.97
   699.4  667.59   767.9   683.2   777.7  685.94   787.5  689.92     807  700.77
   846.2  724.38   934.2  778.66     944  784.43   953.7  789.47   963.5  793.92
#Mann= 3 , 0 , 0
       0      .1       0   435.4    .045       0   464.7     .08       0
Bank Sta=435.4,464.7
XS Rating Curve= 0 ,0
Exp/Cntr=0.3,0.1

Type RM Length L Ch R = 1 ,1336.7  ,334,355.9,370.3
XS GIS Cut Line= 4
     1869419.625      562241.781     1868958.391       562604.18
     1868948.184      563170.492     1869305.655      565510.849
#Sta/Elev= 30
       0  780.86    97.8  730.56   244.4  676.41   332.4  632.99   444.2  623.09
   459.5  620.36   474.2  621.63   664.7  639.08   713.5  651.79   752.6  671.96
   850.2  701.38     987  757.28    1153  795.24  1231.6  819.12  1496.8  920.29
  1703.1  975.91  1889.8 1048.11  1919.2 1052.69  1958.5 1047.18  2056.8 1001.91
    2155  972.45  2243.4  958.37    2489  934.44  2547.9  912.32    2656  858.29
  2734.6  833.21  3196.3   753.1  3284.7  743.77  3412.4  740.09  3520.5  713.24
#Mann= 3 , 0 , 0
       0     .08       0   444.2    .045       0   474.2     .08       0
Bank Sta=444.2,474.2
XS Rating Curve= 0 ,0
Exp/Cntr=0.3,0.1

Type RM Length L Ch R = 1 ,980.6   ,312,307.7,303.5
XS GIS Cut Line= 5
     1869418.376      562132.083     1869025.232      562260.472
     1868806.653      562307.989     1867805.726       562708.35
     1866689.237       565843.54
#Sta/Elev= 30
       0  826.04     125  778.42   192.4  702.46   221.2  685.02   336.6  648.48
     540  615.63   549.7  615.03   578.6  617.83   617.8  627.52   803.9   625.2
   852.9  634.08   911.7  671.24  1146.9  727.92  1254.7  773.72  1450.7  833.46
  1587.9  860.91  1715.3  869.82    1784  860.95  2078.5  748.79  2235.6  706.25
    2432  688.65  2775.6   691.6  3060.3  649.61  3246.8  711.03  3835.8  975.72
  4061.6  995.28  4159.8  969.93  4326.7  907.15  4552.5  857.61  5043.4  673.96
#Mann= 3 , 0 , 0
       0     .06       0     540    .045       0   578.6     .06       0
#XS Ineff= 2 , 0
                          627.66          630.09
Permanent Ineff=
       F       F
Bank Sta=540,578.6
XS Rating Curve= 0 ,0
Exp/Cntr=0.3,0.1

Type RM Length L Ch R = 1 ,672.9   ,310.8,322.1,333.5
XS GIS Cut Line= 5
     1869318.484      561802.711     1868975.613      561940.399
      1868481.73      562148.092     1867882.445      562420.527
     1866765.956      562629.164
#Sta/Elev= 30
       0  827.46    87.5  800.22   194.5   745.9   272.2  696.98   330.6  677.49
   379.2  655.99   418.2  627.53   476.6  616.08   496.1  613.86   515.6  616.92
   564.3  622.09   788.4  622.26   915.1  634.79  1072.3  682.37  1278.6  713.82
  1445.7  749.61  1612.5  790.54  1641.9  792.03  1681.1  803.52  1818.1  828.83
  2072.7  870.21  2111.9  868.93  2170.6  861.01    2200  853.26  2346.9  846.06
  2395.8  830.04  2415.4  829.44  2454.6  840.99  2523.1  879.72  2699.4  956.65
#Mann= 3 , 0 , 0
       0      .1       0   476.6    .045       0   515.6     .06       0
#XS Ineff= 2 , 0
                          765.84          629.64
Permanent Ineff=
       F       F
Bank Sta=476.6,515.6
XS Rating Curve= 0 ,0
Exp/Cntr=0.3,0.1

Type RM Length L Ch R = 1 ,350.7   ,340.5,341.9,343.3
XS GIS Cut Line= 3
     1869097.103      561719.018     1868465.356      561743.316
     1867492.536      561153.319
#Sta/Elev= 30
       0  728.91    68.1  698.12   116.7  688.16   165.4  672.24   233.4  625.42
   252.9  622.35   330.7   622.8   398.8  618.86   418.2  615.01   437.7  613.23
   447.4  613.77   476.6  620.55   573.9  622.82   612.8  626.39   720.5   626.1
   769.5   641.2   808.8  665.39   916.6  724.51   975.5  741.97  1034.4  769.55
    1054  771.77  1171.7  772.18  1220.7  788.09  1289.4  818.07  1436.5  843.88
  1475.7  846.05  1534.6  842.33  1603.2  833.51  1740.5  803.79    1770  791.36
#Mann= 3 , 0 , 0
       0      .1       0   418.2    .045       0   447.4     .06       0
#XS Ineff= 2 , 0
                           612.8           629.1
Permanent Ineff=
       F       F
Bank Sta=418.2,447.4
XS Rating Curve= 0 ,0
Exp/Cntr=0.3,0.1

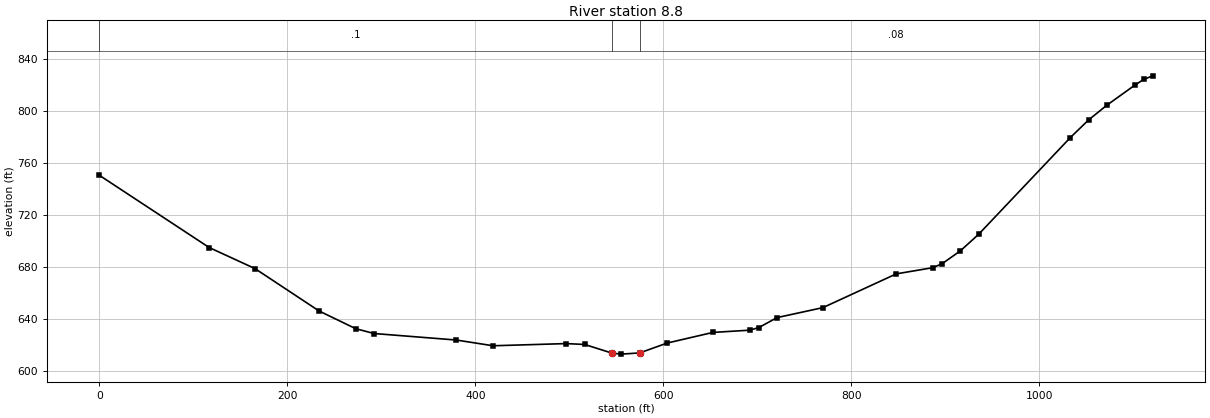
Type RM Length L Ch R = 1 ,8.8     ,6.5,8.8,11
XS GIS Cut Line= 3
     1869247.178      561535.311     1868945.916      561397.745
     1868156.273      561391.988
#Sta/Elev= 30
       0  750.79   116.9  695.19   165.6     679   233.8  646.39   272.7   632.8
   292.2  629.06   379.9  624.04   418.9  619.63   496.9  621.31   516.4  620.62
   545.7  613.92   555.4   613.2   574.9  614.13   604.2  621.73   652.9   629.9
   691.9  631.62   701.6  633.61   721.1   641.3   769.9  648.98   847.9  674.94
   886.9  679.71   896.6  682.71   916.1  692.63   935.6  705.42  1033.1  779.78
  1052.6  793.39  1072.1  804.75  1101.4  819.94  1111.1  824.51  1120.8  827.29
#Mann= 3 , 0 , 0
       0      .1       0   545.7    .045       0   574.9     .08       0
Bank Sta=545.7,574.9
XS Rating Curve= 0 ,0
Exp/Cntr=0.3,0.1

Chan Stop Cuts=-1
Use User Specified Reach Order=0
Composite Channel Slope=5